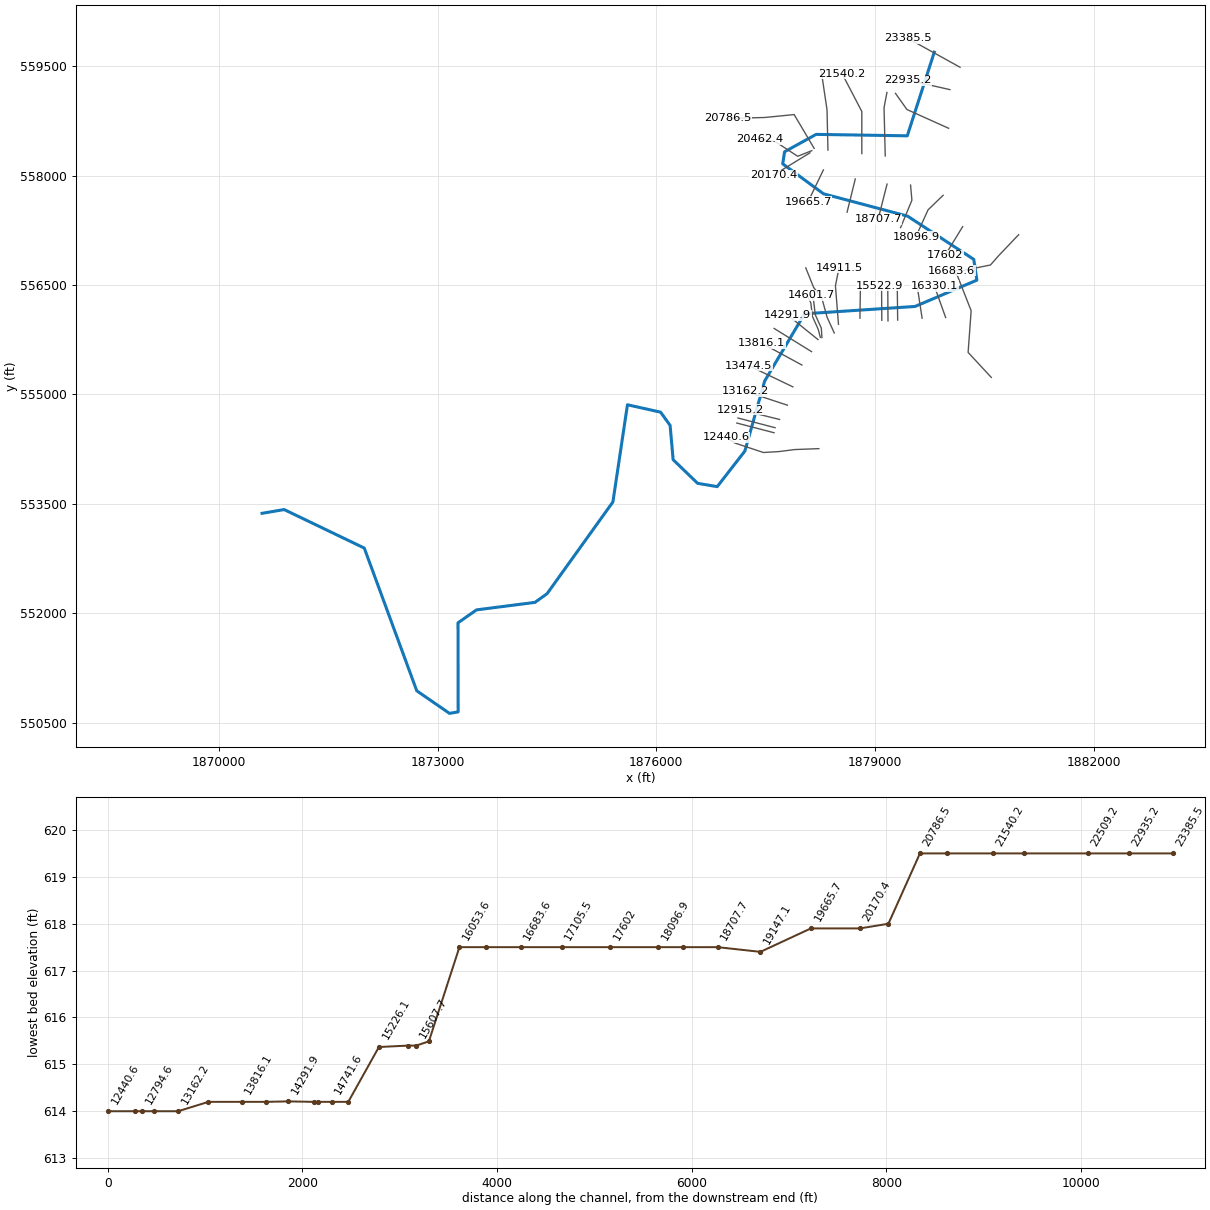
--- BIGSANDYCR.prj (project) ---

Proj Title=BIGSANDYCR
Current Plan=p01
Default Exp/Contr=0,0
English Units
Geom File=g01
Flow File=f01
Plan File=p01
BEGIN DESCRIPTION:
END DESCRIPTION:
DSS Export Rating Curves= 0
DSS Export Rating Curve Sorted= 0
DSS Export Volume Flow Curves= 0
DXF OffsetX= 0
DXF OffsetY= 0
DXF ScaleX= 0
DXF ScaleY= 0

--- BIGSANDYCR.p01 (plan) ---

Plan Title=Floodplain
Program Version=4.00
Geom File=g01
Flow File=f01
K Sum by GR=0
Std Step Tol=0.01
Critical Tol=0.01
Num of Std Step Trials=20
Max Error Tol=0.3
Flow Tol Ratio=0.001
Split Flow NTrial=30
Split Flow Tol=0.02
Split Flow Ratio=0.02
Log Output Level=0
Friction Slope Method=1
Unsteady Friction Slope Method=2
Unsteady Bridges Friction Slope Method=1
Global Log Level=0
CheckData=False
Run HTab=0
Run UNet=0
Run PostProcess=0
UNET Theta=0
UNET Theta Warmup=0
UNET ZTol=0
UNET ZSATol=0
UNET MxIter=0
UNET MaxInSteps=0
UNET DtIC=0
UNET DtMin=0
UNET MaxCRTS=0
UNET WFStab=0
UNET SFStab=0
UNET WFX=0
UNET SFX=0
UNET DSS MLevel=0
UNET DZMax Abort=0
UNET Convert EG Bridges=0
UNET Use Existing IB Tables=0
UNET Froude Limit=0
UNET Froude Power=0
Write IC File=0
Echo Input=False
Echo Output=False
Write Detailed=0

--- BIGSANDYCR.f01 (steady flow) ---

Flow Title=NFF Regression Equation
Program Version=4.10
Number of Profiles= 1
Profile Names=P100yr
River Rch & RM=BIGSANDYCR,Main            ,23385.5
11476.25
River Rch & RM=BIGSANDYCR,Main            ,16330.1
11857.02
River Rch & RM=BIGSANDYCR,Main            ,12145.4
11902.95
River Rch & RM=BIGSANDYCR,Main            ,6822.8
11974.73
Boundary for River Rch & Prof#=BIGSANDYCR,Main            , 1
Up Type= 0
Dn Type= 1
Dn Known WS=630.5
DSS Import GetInterval= 0
DSS Import GetPeak= 0
DSS Import FillOption= 0

--- BIGSANDYCR.g01 (geometry) ---

Geom Title=USGS 10m DEM
Program Version=4.10

River Reach=BIGSANDYCR      ,Main
Reach XY= 30
     1879813.491       559691.07     1879442.771      558544.302
     1878192.771      558564.094      1877759.79      558325.725
      1877734.41      558160.227     1878293.813       557749.51
     1879446.938       557443.26     1880355.329      556850.552
     1880397.787      556566.211     1879549.311      556205.375
     1878033.686      556104.681     1877486.384      555182.894
     1877214.815      554222.911     1876835.986      553735.713
     1876567.113      553780.985     1876231.176      554104.769
     1876189.509      554575.255      1876059.52      554756.181
     1875604.434      554857.733     1875404.936      553525.731
     1874502.356      552269.179     1874335.986      552149.342
     1873533.606      552046.262     1873280.245      551869.035
     1873282.048      550648.392     1873163.308      550627.847
     1872714.306      550937.166     1871994.407      552893.699
      1870895.39      553421.349     1870592.208      553369.979

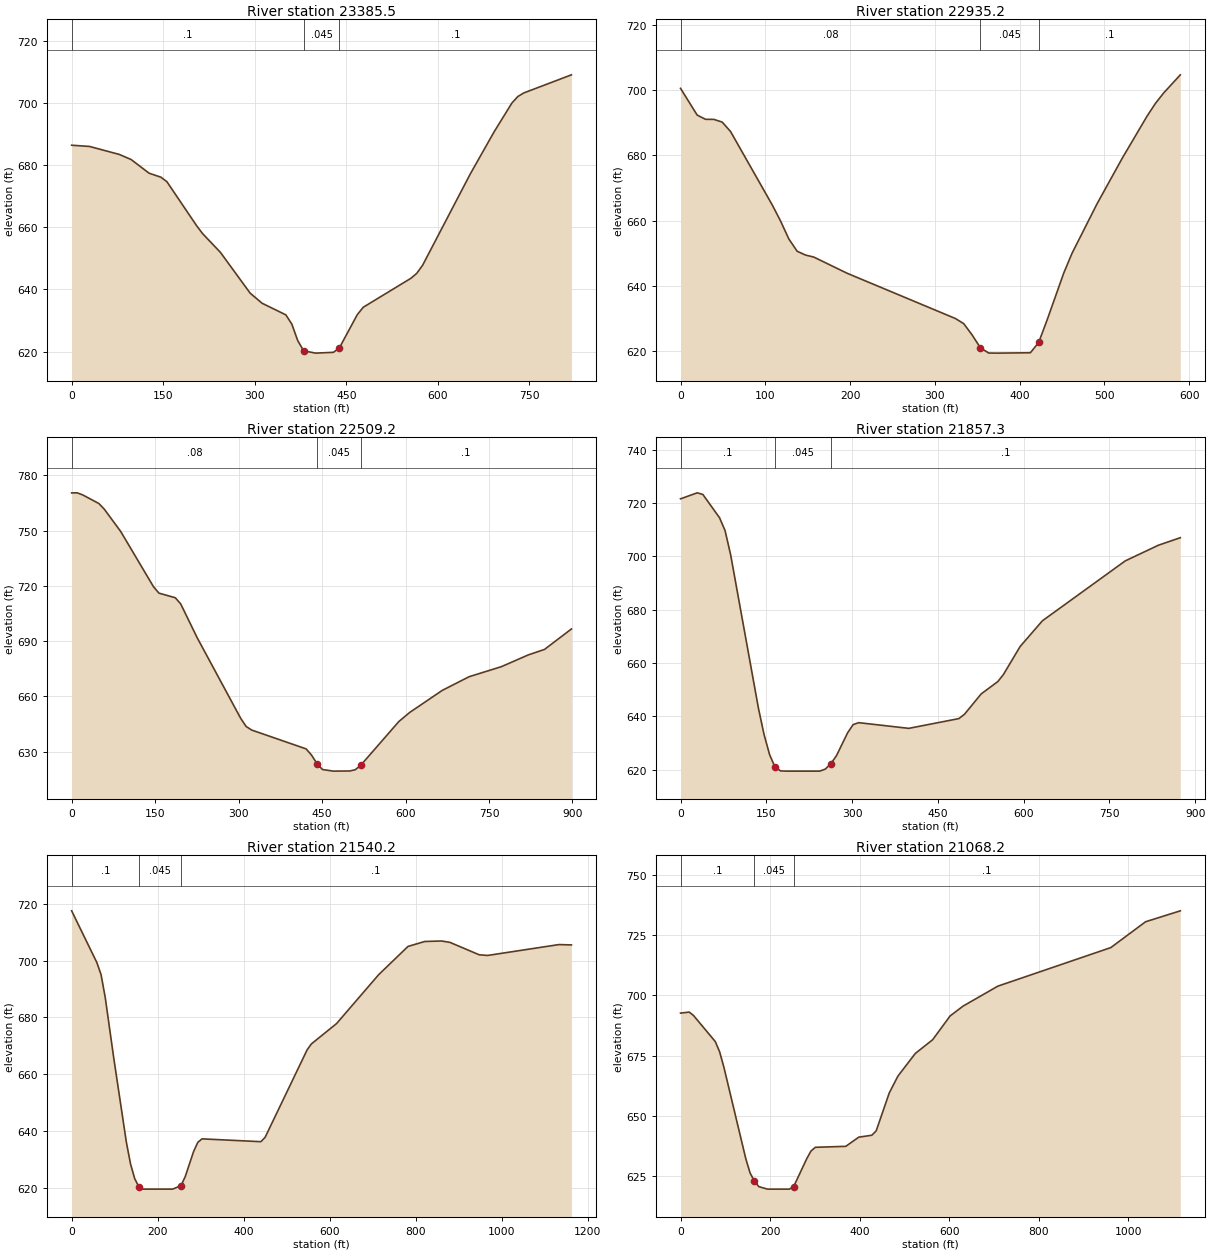
Type RM Length L Ch R = 1 ,23385.5 ,444,450.3,456.7
XS GIS Cut Line= 3
     1880166.977      559484.096      1879808.65      559682.319
     1879450.324      559880.543
#Sta/Elev= 30
       0  686.48    29.2  686.09      78  683.52    97.5  681.87   126.8  677.48
   146.2  676.18     156  674.75   204.8  660.55   214.5  658.02   243.8  651.96
   292.5  638.83     312  635.58     351  631.83   360.8  628.85   370.5  623.53
   380.2  620.25   399.8   619.5     429  619.76   438.8  621.21     468  631.87
   477.8  634.27   555.8  643.59   565.5   645.2   575.2  647.84   653.2  677.21
   692.2  690.76   721.5  700.09   731.2  702.17     741  703.33     819  709.16
#Mann= 3 , 0 , 0
       0      .1       0   380.2    .045       0   438.8      .1       0
Bank Sta=380.2,438.8
XS Rating Curve= 0 ,0
Exp/Cntr=0.3,0.1

Type RM Length L Ch R = 1 ,22935.2 ,430.5,426,421.5
XS GIS Cut Line= 2
     1880027.692      559177.341     1879452.866      559308.423
#Sta/Elev= 30
       0  700.54    19.6  692.37    29.5  691.06    39.3  691.04    49.1  690.22
      59  687.33   108.1   664.9   117.9  659.99   127.7  654.48   137.6  650.68
   147.4  649.52   157.2   648.9   196.5  643.95   324.3  630.09   334.1  628.52
   343.9   625.1   353.8  621.11   363.6  619.53   373.4   619.5   412.7  619.61
   422.5  622.76   432.4   629.6     452  643.95   461.8  650.03   491.3  665.17
   520.8  679.02   550.3  692.01   560.1  695.88   569.9  699.11   589.6  704.68
#Mann= 3 , 0 , 0
       0     .08       0   353.8    .045       0   422.5      .1       0
Bank Sta=353.8,422.5
XS Rating Curve= 0 ,0
Exp/Cntr=0.3,0.1

Type RM Length L Ch R = 1 ,22509.2 ,677.2,651.8,626.4
XS GIS Cut Line= 3
     1880010.132      558647.674     1879438.112      558905.024
     1879281.168      559125.857
#Sta/Elev= 30
       0  770.46     9.8  770.51    19.6  769.42      49   764.7    58.8  761.59
    88.2  749.52     147  719.61   156.8  716.08   186.2  713.59     196  710.23
   225.4     692   303.8  648.14   313.6  643.73   323.4  641.81   421.4  631.56
   431.2  628.17     441  623.52   450.8  620.37   470.4   619.5   499.8  619.58
   509.6  620.24   519.4  622.63     588   646.4   607.6  651.36     666   663.3
   714.3  670.73   772.4  676.19   820.8  682.58   849.8  685.53   898.2  696.64
#Mann= 3 , 0 , 0
       0     .08       0     441    .045       0   519.4      .1       0
Bank Sta=441,519.4
XS Rating Curve= 0 ,0
Exp/Cntr=0.3,0.1

Type RM Length L Ch R = 1 ,21857.3 ,317.6,317.1,316.5
XS GIS Cut Line= 3
     1879140.687      558268.508     1879124.223      558930.371
     1879163.807      559138.704
#Sta/Elev= 30
       0  721.55    29.2   723.8      39   723.2    68.2  714.47    77.9  709.64
    87.6  700.62   136.3  643.02     146  633.28   155.8  625.66   165.5  620.89
   175.2  619.58     185   619.5   243.4   619.5   253.1  620.25   262.9  622.31
   272.6  625.24   292.1  633.81   301.8  636.92   311.6  637.66   399.2  635.53
   486.8  639.19   496.6  640.81   525.8  648.43     555  653.08   564.7   655.7
   593.9  666.19   632.9  675.84   777.7  698.28   835.6  704.15   874.1  706.98
#Mann= 3 , 0 , 0
       0      .1       0   165.5    .045       0   262.9      .1       0
Bank Sta=165.5,262.9
XS Rating Curve= 0 ,0
Exp/Cntr=0.3,0.1

Type RM Length L Ch R = 1 ,21540.2 ,471.5,472,472.5
XS GIS Cut Line= 4
     1878819.362       558300.51     1878819.362      558877.593
     1878706.862       559094.26     1878548.529      559396.343
#Sta/Elev= 30
       0   717.6    58.7  699.34    68.5  695.05    78.2  686.95    97.8  665.83
   127.2  636.08   136.9   628.4   146.7  623.18   156.5  620.26   166.3   619.5
   234.8   619.5   254.3  620.72   264.1   623.9   283.6  632.75   293.4     636
   303.2  637.22   440.2  636.22   449.9  637.76   547.7  668.62   557.5  670.68
   616.1  677.86   713.8  695.06   782.2  705.05   821.2  706.79   860.2  706.97
   879.7  706.48   947.9   702.1   967.4  701.87    1133   705.7  1162.3  705.58
#Mann= 3 , 0 , 0
       0      .1       0   156.5    .045       0   254.3      .1       0
Bank Sta=156.5,254.3
XS Rating Curve= 0 ,0
Exp/Cntr=0.3,0.1

Type RM Length L Ch R = 1 ,21068.2 ,270.1,281.7,293.2
XS GIS Cut Line= 3
     1878354.779      558348.427     1878341.926      558902.002
     1878258.946      559458.843
#Sta/Elev= 30
       0  692.64    19.4  693.06    29.1  691.63    77.7   680.8    87.4  676.55
    97.1     670   145.7  632.22   155.4  626.21   165.2   622.8   174.9  620.54
   194.3   619.5   242.9   619.5   252.6  620.48   281.7  632.04   291.4  635.31
   301.2  636.88   369.2  637.28   398.3   641.1   427.4  641.89   437.2  643.72
   466.3  659.43   485.7  666.46   524.6  675.88   563.4  681.59   602.3  691.45
   631.4  695.56     709  703.84   961.4  719.86  1039.1   730.6  1116.7  735.14
#Mann= 3 , 0 , 0
       0      .1       0   165.2    .045       0   252.6      .1       0
Bank Sta=165.2,252.6
XS Rating Curve= 0 ,0
Exp/Cntr=0.3,0.1

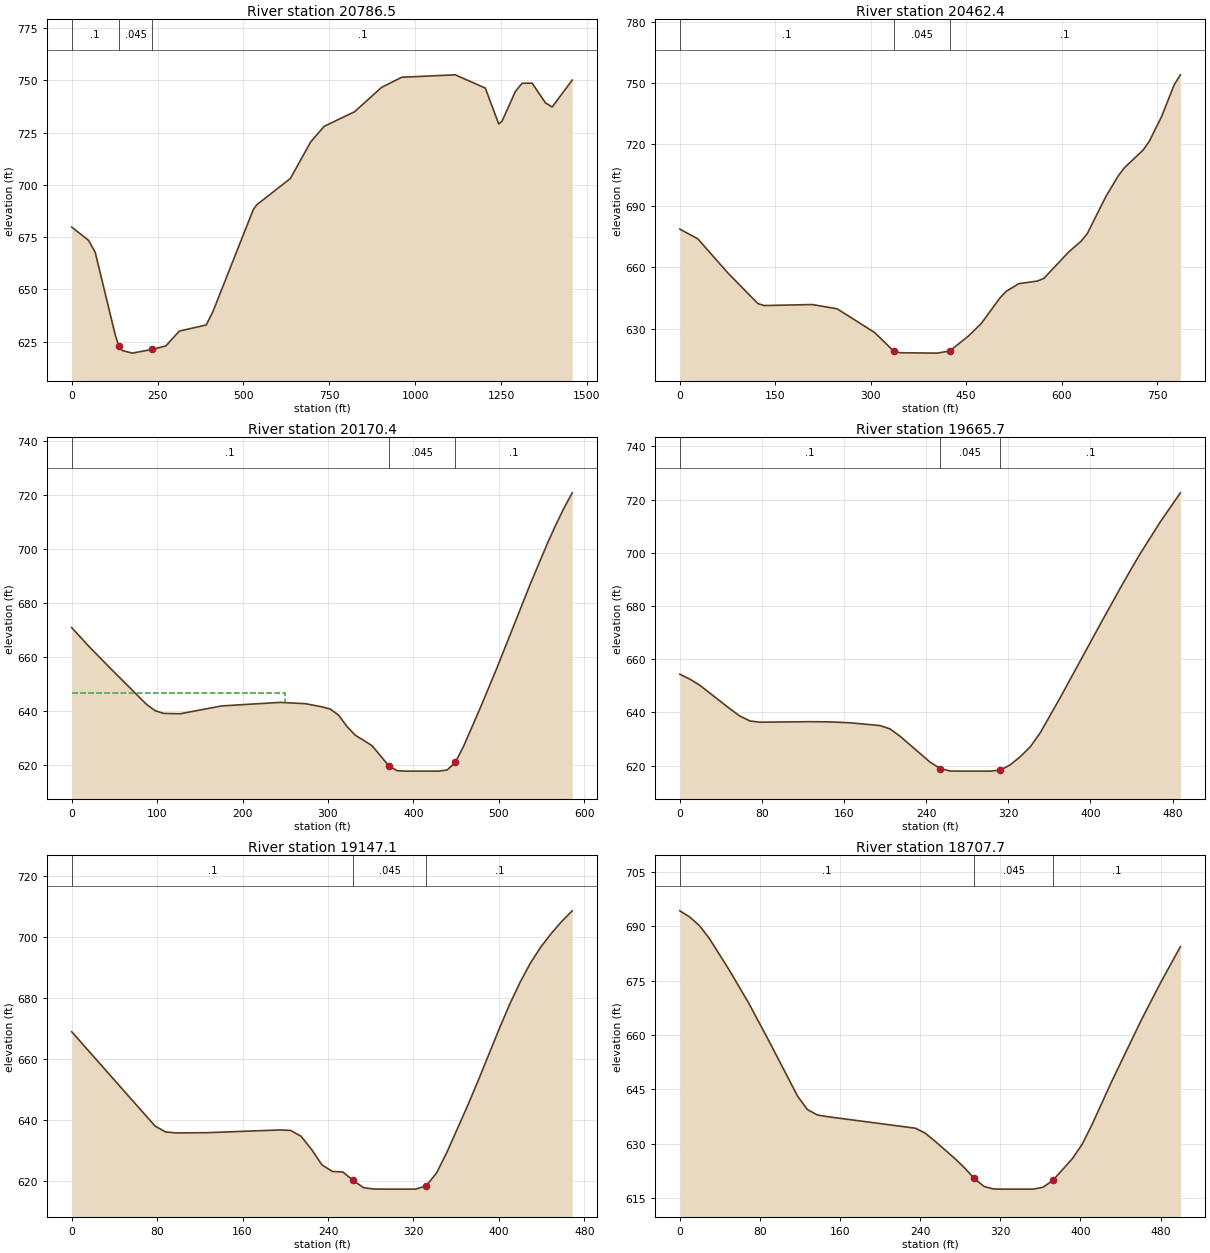
Type RM Length L Ch R = 1 ,20786.5 ,312.8,324.1,334.2
XS GIS Cut Line= 4
     1878165.543      558372.038     1877891.237      558835.579
     1877490.196      558795.649     1876974.571       558781.76
#Sta/Elev= 30
       0  679.83      49  673.52    68.6  667.72   127.3  627.89   137.1  623.04
   146.9  620.77   176.3   619.5     235   621.3   274.2  622.96   313.4  630.05
   391.7  632.98   411.3   639.4   528.8  688.22   538.6  690.47   636.9  703.11
   695.9  720.61   735.2  728.06   823.7  735.04   902.3  746.71   961.1  751.56
  1116.8  752.71  1204.4  746.37  1243.4  729.18  1253.1  730.53    1292  744.76
  1311.5  748.69  1340.7  748.71  1379.6  739.27  1399.1  737.32  1457.5  750.22
#Mann= 3 , 0 , 0
       0      .1       0   137.1    .045       0     235      .1       0
Bank Sta=137.1,235
XS Rating Curve= 0 ,0
Exp/Cntr=0.3,0.1

Type RM Length L Ch R = 1 ,20462.4 ,267.2,292.1,317.6
XS GIS Cut Line= 4
     1878132.572      558340.705     1877939.382      558264.042
     1877634.775      558463.365     1877423.185      558499.141
#Sta/Elev= 30
       0   678.6    28.3  673.83    75.6  657.13   122.8  642.18   132.3  641.24
   207.8  641.74   247.2  639.65   306.2  628.04   335.8  619.05   345.6   618.2
   404.6     618   424.3  619.08   453.8  626.45   473.5  632.44     503  644.98
   512.8  648.17   532.5  651.93     562  653.22   571.9  654.51   610.9  667.38
   630.4  672.65   640.2  676.39   669.4  694.49   688.9  704.61   698.7  708.59
   727.9  717.19   737.7  721.51   757.2  733.73   776.7  749.04   786.5  753.95
#Mann= 3 , 0 , 0
       0      .1       0   335.8    .045       0   424.3      .1       0
Bank Sta=335.8,424.3
XS Rating Curve= 0 ,0
Exp/Cntr=0.3,0.1

Type RM Length L Ch R = 1 ,20170.4 ,491.6,504.7,517.5
XS GIS Cut Line= 2
     1878108.251      558311.274     1877608.251      558005.718
#Sta/Elev= 30
       0  670.97    19.5  664.22    48.8  654.79    87.9   642.5    97.7  640.24
   107.4  639.25     127  639.11   175.8  642.01   244.2  643.31   273.4  642.84
     293  641.66   302.8  640.83   312.5  638.58   322.3  634.39     332  631.18
   351.6  627.33   371.1  619.92   380.9  618.05   390.6   617.9   429.7   617.9
   439.5  618.32   449.2  621.16     459  627.24   478.5  641.39   498.1  656.26
   537.1  687.24   556.7   701.9   566.4  708.69   576.2  715.06     586  720.77
#Mann= 3 , 0 , 0
       0      .1       0   371.1    .045       0   449.2      .1       0
#XS Ineff= 2 , 0
          249.45   646.6
Permanent Ineff=
       F       F
Bank Sta=371.1,449.2
XS Rating Curve= 0 ,0
Exp/Cntr=0.3,0.1

Type RM Length L Ch R = 1 ,19665.7 ,513.9,518.6,523.2
XS GIS Cut Line= 2
     1878292.279      558076.899     1878080.473      557637.663
#Sta/Elev= 30
       0  654.35     9.8  652.51    19.5  650.19    48.8  641.35    58.5  638.62
    68.3  636.77      78   636.3   126.8   636.5   146.3  636.42   165.8  636.08
     195  635.03   204.8  633.77   214.6     631   243.8  621.28   253.6  618.87
   263.3  617.95   273.1   617.9   302.3   617.9   312.1  618.29   321.8  620.25
   331.6  623.32   341.4  627.06   351.1  632.33   370.6  645.59   409.6  673.19
   429.1  686.76   438.9   693.4   448.6  699.79   468.1  711.68   487.6  722.57
#Mann= 3 , 0 , 0
       0      .1       0   253.6    .045       0   312.1      .1       0
Bank Sta=253.6,312.1
XS Rating Curve= 0 ,0
Exp/Cntr=0.3,0.1

Type RM Length L Ch R = 1 ,19147.1 ,439.5,439.4,439.2
XS GIS Cut Line= 2
     1878729.574      557952.839     1878617.136      557497.834
#Sta/Elev= 30
       0  668.99    78.1  638.06    87.9  636.15    97.6  635.82   126.9   635.9
   195.3   636.8     205  636.64   214.8  634.73   224.6  630.41   234.4  625.32
   244.1   623.2   253.9  623.02   263.6  620.24   273.4  617.86   283.2  617.43
   292.9   617.4   322.2   617.4     332  618.47   341.8  622.78   351.5   629.6
     371  644.97   380.8  653.12   400.3  669.92   410.1  677.96   419.9  685.23
   429.6  691.52   439.4  696.82   449.2  701.26   458.9  705.16   468.7  708.61
#Mann= 3 , 0 , 0
       0      .1       0   263.6    .045       0     332      .1       0
Bank Sta=263.6,332
XS Rating Curve= 0 ,0
Exp/Cntr=0.3,0.1

Type RM Length L Ch R = 1 ,18707.7 ,359.2,356,352.8
XS GIS Cut Line= 2
     1879165.543      557882.454     1879042.279      557398.079
#Sta/Elev= 30
       0  694.29     9.8  692.61    19.6   690.2    29.4   686.7      49  678.11
    68.6  668.92    88.2  658.79   117.6  643.15   127.4  639.45   137.2  637.98
     147  637.51   235.2  634.31     245  632.96   254.8  630.73   274.4     626
   284.2  623.39     294  620.44   303.8  618.23   313.6  617.52   323.4   617.5
   352.8   617.5   362.6  618.01   372.4   619.9     392  625.93   401.8  629.91
   411.6  635.33   431.2   647.2   460.6  664.06   480.2  674.55   499.8  684.39
#Mann= 3 , 0 , 0
       0      .1       0     294    .045       0   372.4      .1       0
Bank Sta=294,372.4
XS Rating Curve= 0 ,0
Exp/Cntr=0.3,0.1

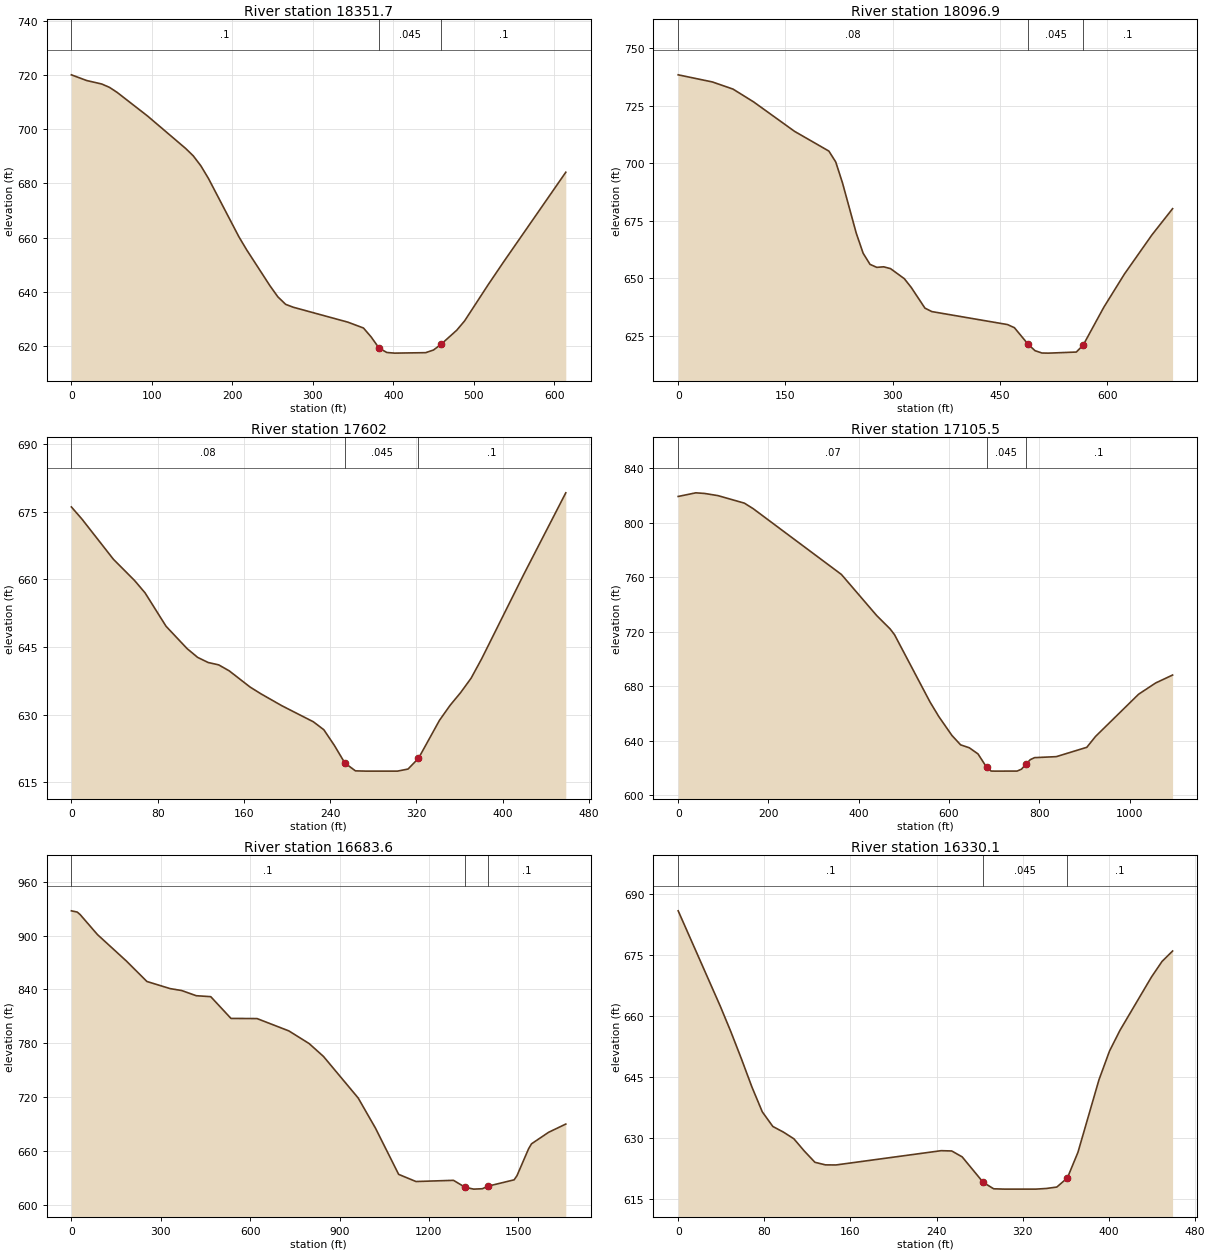
Type RM Length L Ch R = 1 ,18351.7 ,255.6,254.8,254.1
XS GIS Cut Line= 3
     1879488.081      557869.062     1879506.399      557661.737
     1879351.191       557286.39
#Sta/Elev= 30
       0     720    18.9  717.91    37.8  716.61    47.3  715.39    56.8  713.54
    94.6  704.84   141.9   692.9   151.4  690.17   160.8  686.52   170.3  681.84
   208.1  660.37   217.8  655.54   246.8  642.28   256.5  638.25   266.2  635.47
   275.8  634.39   343.5  628.91   362.9  626.75   372.5  623.44   382.2  619.38
   391.9  617.74   401.6   617.5   440.2  617.67   449.9  618.64   459.6  620.82
   478.9  625.96   488.6  629.38   517.6  642.58   536.9  651.04   614.3  684.12
#Mann= 3 , 0 , 0
       0      .1       0   382.2    .045       0   459.6      .1       0
Bank Sta=382.2,459.6
XS Rating Curve= 0 ,0
Exp/Cntr=0.3,0.1

Type RM Length L Ch R = 1 ,18096.9 ,497.7,494.9,492
XS GIS Cut Line= 3
     1879934.524      557729.098     1879727.927      557529.445
      1879561.26       557161.39
#Sta/Elev= 30
       0  738.34    47.9  735.24    76.6  732.15   105.3  726.62   162.8  713.78
   210.7  705.23   220.3   700.5   229.8  691.35     249  669.57   258.6  660.88
   268.2  656.05   277.7  654.74   287.3  654.98   296.9  654.19   316.2  649.82
   325.8  646.05     345  637.05   354.6  635.54   460.5   629.9   470.1  628.55
   489.3  621.35   498.9  618.57   508.6  617.55   518.2   617.5   556.7  617.97
   566.3     621   595.1   637.4     624  651.86   662.5  668.87   691.3  680.22
#Mann= 3 , 0 , 0
       0     .08       0   489.3    .045       0   566.3      .1       0
Bank Sta=489.3,566.3
XS Rating Curve= 0 ,0
Exp/Cntr=0.3,0.1

Type RM Length L Ch R = 1 ,17602   ,514.9,496.5,477.7
XS GIS Cut Line= 2
     1880202.929      557299.884     1879963.344      556908.959
#Sta/Elev= 30
       0  676.08     9.8  673.39      39  664.47    58.5  659.79    68.3  657.04
    87.8  649.62   107.3  644.67   117.1  642.72   126.8  641.59   136.6  641.06
   146.3  639.75   165.8  636.13   175.6  634.67   195.1  632.01   224.4  628.44
   234.1  626.68   243.9   623.2   253.6   619.3   263.4  617.56   273.2   617.5
   302.4   617.5   312.2  617.96   321.9  620.34   341.4  628.78   351.2  632.09
     361  634.92   370.7  638.11   380.5  642.42   419.5  661.11   458.5  679.21
#Mann= 3 , 0 , 0
       0     .08       0   253.6    .045       0   321.9      .1       0
Bank Sta=253.6,321.9
XS Rating Curve= 0 ,0
Exp/Cntr=0.3,0.1

Type RM Length L Ch R = 1 ,17105.5 ,453.1,422,389.8
XS GIS Cut Line= 5
     1880970.466      557188.922     1880694.038       556898.82
     1880583.711      556773.376     1880186.746      556693.612
     1880064.871      556706.112
#Sta/Elev= 30
       0  819.41    39.1  822.08    58.6  821.62      88  820.03   146.6   814.5
   166.2  810.42   361.6  762.06     440  731.76   469.5  722.02   479.3  717.74
     558  668.23   577.4  657.58   606.3  643.77   625.6  636.82   644.9  634.66
   664.2  630.14   683.5  620.21   693.1  617.56   702.7   617.5   750.9  617.54
   760.6  618.97   770.2  622.51   779.9  625.92   789.5  627.41   837.7  628.15
   905.2  635.02   924.5     643  1019.8     674  1057.5  682.27  1095.2  688.14
#Mann= 3 , 0 , 0
       0     .07       0   683.5    .045       0   770.2      .1       0
Bank Sta=683.5,770.2
XS Rating Curve= 0 ,0
Exp/Cntr=0.3,0.1

Type RM Length L Ch R = 1 ,16683.6 ,354.1,353.4,352.6
XS GIS Cut Line= 5
     1880595.466       555232.73     1880277.411      555575.786
     1880319.038      556146.737     1880131.538      556624.862
     1880052.478      556694.777
#Sta/Elev= 30
       0  927.64    19.5  926.27    29.2  923.54    87.7  901.11   185.2  871.52
   253.4  848.91   331.4  840.96   370.4  838.79   419.1  833.04   467.8  831.97
   535.7  807.72   623.1  807.57   729.8  793.84   797.7  779.79   846.2  765.34
   962.6  719.06  1020.9   685.3  1098.4  633.96  1156.6  625.97  1282.5   627.3
  1321.3  619.57  1350.4   617.5  1379.4  617.94  1398.8  620.83    1486  627.87
  1495.7  632.58  1534.5  662.43  1544.2  667.96  1601.8  680.85  1659.4     690
#Mann= 3 , 0 , 0
       0      .1       0  1321.3    .045       0  1398.8      .1       0
Bank Sta=1321.3,1398.8
XS Rating Curve= 0 ,0
Exp/Cntr=0.3,0.1

Type RM Length L Ch R = 1 ,16330.1 ,280.9,276.6,272.2
XS GIS Cut Line= 2
     1879969.246      556053.751     1879814.733      556486.042
#Sta/Elev= 30
       0  685.91    39.1  662.46    48.8  656.27    58.6  649.61    68.4  642.65
    78.1   636.5    87.9   632.9    97.7  631.52   107.4  629.88   117.2  626.84
     127  624.09   136.8  623.46   146.5  623.44   244.2  626.95     254  626.88
   263.7  625.43   283.3  619.14     293  617.58   302.8   617.5   332.1   617.5
   341.9  617.66   351.6  618.01   361.4  620.25   371.2  626.54   390.7  644.35
   400.5  651.43   410.2  656.52   439.5  669.65   449.3  673.47   459.1  676.03
#Mann= 3 , 0 , 0
       0      .1       0   283.3    .045       0   361.4      .1       0
Bank Sta=283.3,361.4
XS Rating Curve= 0 ,0
Exp/Cntr=0.3,0.1

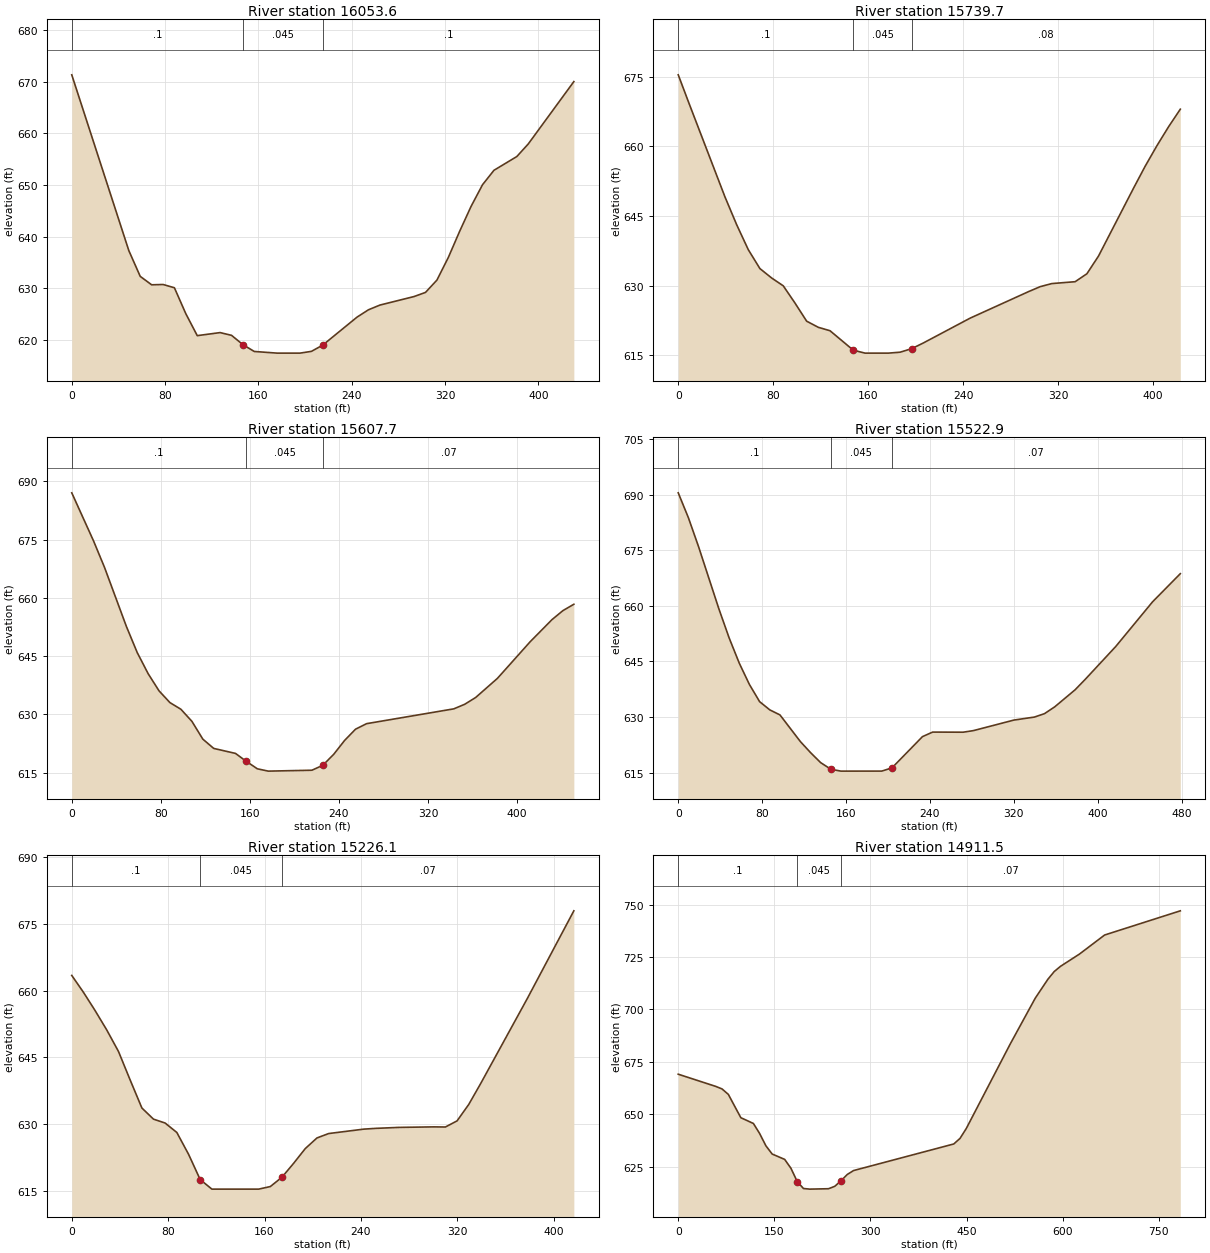
Type RM Length L Ch R = 1 ,16053.6 ,317,313.9,310.8
XS GIS Cut Line= 2
     1879646.121      556044.654     1879581.263      556470.227
#Sta/Elev= 30
       0  671.31    48.9  637.34    58.7  632.34    68.5  630.71    78.3  630.77
      88  630.14    97.8  625.12   107.6  620.88   127.2  621.47     137  620.94
   146.8  619.13   156.5  617.82   176.1   617.5   195.7   617.5   205.5  617.84
   215.2  619.05   244.6  624.46   254.4  625.88   264.2  626.79   293.5  628.44
   303.3  629.24   313.1  631.62   322.9  636.01   332.6  641.06   342.4  645.88
   352.2  650.06     362  652.85   381.6  655.51   391.4  657.94   430.5     670
#Mann= 3 , 0 , 0
       0      .1       0   146.8    .045       0   215.2      .1       0
Bank Sta=146.8,215.2
XS Rating Curve= 0 ,0
Exp/Cntr=0.3,0.1

Type RM Length L Ch R = 1 ,15739.7 ,132.1,132,131.8
XS GIS Cut Line= 2
     1879311.231      556018.614     1879306.023      556441.531
#Sta/Elev= 30
       0  675.42     9.8   668.8    39.3  649.18    49.2  643.16      59  637.78
    68.8   633.7    78.7  631.67    88.5  629.98    98.4  626.26   108.2  622.37
     118  621.05   127.9  620.31   147.5  616.12   157.4  615.49     177  615.49
   186.9  615.69   196.7  616.45   206.6  617.69   245.9  623.02   295.1  628.73
   304.9   629.8   314.8  630.47   334.4  630.87   344.3  632.58   354.1   636.4
   383.6  651.01   393.4  655.74   403.3  660.16   413.1  664.23     423  668.02
#Mann= 3 , 0 , 0
       0      .1       0   147.5    .045       0   196.7     .08       0
Bank Sta=147.5,196.7
XS Rating Curve= 0 ,0
Exp/Cntr=0.3,0.1

Type RM Length L Ch R = 1 ,15607.7 ,84.8,84.8,84.8
XS GIS Cut Line= 2
     1879178.426      556007.712     1879175.301      556458.753
#Sta/Elev= 30
       0  687.07    19.6  674.66    29.4  667.88      49  652.71    58.8  645.93
    68.6   640.5    78.4  636.07    88.2  633.04      98  631.34   107.9  628.23
   117.7  623.65   127.5  621.25   147.1  619.96   156.9  617.89   166.7     616
   176.5   615.4   215.7  615.63   225.5   616.9   235.3  619.73   245.1  623.31
   254.9   626.2   264.8  627.62   343.2  631.44     353  632.62   362.8  634.36
   382.4   639.3   411.8  648.73   431.4  654.42   441.2  656.74     451  658.37
#Mann= 3 , 0 , 0
       0      .1       0   156.9    .045       0   225.5     .07       0
Bank Sta=156.9,225.5
XS Rating Curve= 0 ,0
Exp/Cntr=0.3,0.1

Type RM Length L Ch R = 1 ,15522.9 ,297.3,296.8,296.3
XS GIS Cut Line= 3
     1879093.564      556016.253     1879090.674      556433.482
     1879066.618      556490.151
#Sta/Elev= 30
       0  690.54     9.7  683.81    19.4  675.99    38.8  659.18    48.5   651.4
    58.2  644.55    67.9  638.79    77.6  634.16    87.3  631.94      97  630.58
   116.4  623.41   126.1  620.42   135.8   617.7   145.6   615.9   155.2   615.4
   194.1  615.41   203.8  616.27   232.9  624.71   242.6  625.94   271.7  625.91
   281.4  626.33   320.2  629.19   339.6  629.99   349.3  630.92     359  632.75
   378.4  637.34   388.1  640.17   417.2  649.04   452.4  661.13   478.8  668.71
#Mann= 3 , 0 , 0
       0      .1       0   145.6    .045       0   203.8     .07       0
Bank Sta=145.6,203.8
XS Rating Curve= 0 ,0
Exp/Cntr=0.3,0.1

Type RM Length L Ch R = 1 ,15226.1 ,312.5,314.6,316.7
XS GIS Cut Line= 2
     1878793.523      556044.656     1878799.773      556461.323
#Sta/Elev= 30
       0  663.39     9.7   659.6    19.4  655.48    29.1  651.11    38.8  646.29
    48.5  639.87    58.2   633.6    67.8   631.1    77.5  630.22    87.2   628.1
    96.9  623.22   106.6  617.51   116.3  615.37   155.1  615.37   164.8  615.95
   174.4  618.03   184.1  621.16   193.8  624.48   203.5  626.87   213.2  627.86
   242.3  628.85     252  629.02   271.4  629.24   300.4  629.36   310.1  629.33
   319.8  630.71   329.5  634.41   339.2  639.01     378  658.16   416.7  677.91
#Mann= 3 , 0 , 0
       0      .1       0   106.6    .045       0   174.4     .07       0
Bank Sta=106.6,174.4
XS Rating Curve= 0 ,0
Exp/Cntr=0.3,0.1

Type RM Length L Ch R = 1 ,14911.5 ,165.7,170,174.3
XS GIS Cut Line= 3
     1878499.246       555961.32      1878457.58      556487.362
     1878506.538      556738.404
#Sta/Elev= 30
       0  669.09    58.6  663.26    68.4  662.05    78.2  659.44    97.7  648.31
   117.3  645.56     127  640.78   136.8   634.9   146.6  630.96   166.1   628.4
   175.9  624.16   185.7  617.81   195.4   614.5   205.2   614.2   234.5  614.39
   244.3  615.55   254.1  618.22   263.8   621.2   273.6  623.07     430  635.77
   439.7  638.42   449.5  643.15   517.9  683.41   557.2  705.44   576.9  714.45
   586.7  718.11   596.6  720.63   626.1  726.46   665.4  735.57   783.5  747.12
#Mann= 3 , 0 , 0
       0      .1       0   185.7    .045       0   254.1     .07       0
Bank Sta=185.7,254.1
XS Rating Curve= 0 ,0
Exp/Cntr=0.3,0.1

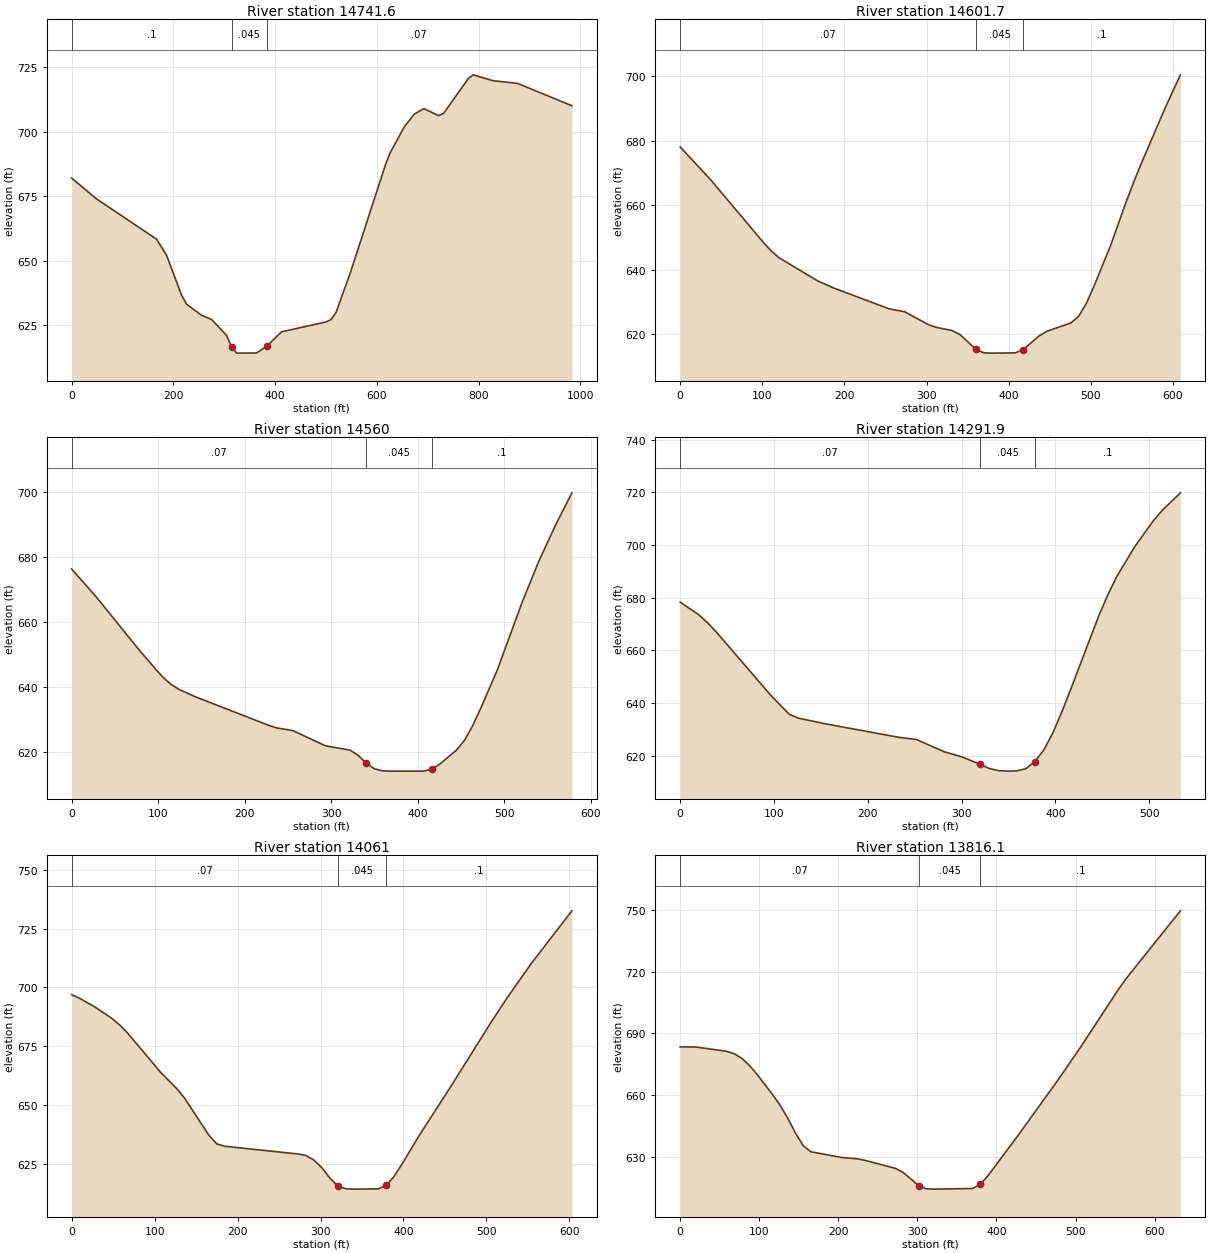
Type RM Length L Ch R = 1 ,14741.6 ,143.4,139.9,136.4
XS GIS Cut Line= 5
      1878441.62      555841.739     1878343.703      556056.323
     1878270.787      556320.906     1878159.328      556464.656
      1878050.49      556734.439
#Sta/Elev= 30
       0  681.97    49.1  673.89   167.1   658.3   186.7  652.01   216.2  636.54
     226  633.11   255.5  628.84   275.1  627.22   304.5  621.04   314.3  616.61
   324.1   614.2   363.3  614.26   382.9  616.78   412.3  622.44   500.5   626.3
   510.3  627.28   519.9  630.09   548.6  645.88   615.6  686.49   625.2  691.52
   653.9   701.9   673.1  706.71   692.2   708.9   721.3  706.17     731  707.05
   779.5  720.52   789.2  721.97     828  719.69   876.5  718.65   983.1     710
#Mann= 3 , 0 , 0
       0      .1       0   314.3    .045       0   382.9     .07       0
Bank Sta=314.3,382.9
XS Rating Curve= 0 ,0
Exp/Cntr=0.3,0.1

Type RM Length L Ch R = 1 ,14601.7 ,41.7,41.7,41.7
XS GIS Cut Line= 5
     1878272.176      555779.413     1878263.842       555908.58
     1878180.377      556092.193     1878158.628      556283.713
     1878122.523       556361.01
#Sta/Elev= 30
       0  678.12      37  667.98   101.7  648.41   110.9   645.9   120.2   643.8
   167.8  636.54   187.1  634.38   254.3  627.94   273.5  627.02   302.3  623.02
   311.9  622.18   331.1  621.22   340.8  619.95     360  615.41   369.7   614.3
   379.3   614.2   408.2  614.28   417.9  615.31   437.1  619.53   446.8  620.98
   475.7  623.55   485.3  625.61     495  629.78   504.6  635.35   523.9  647.39
   542.8  660.84   552.3   667.2   561.8  673.14   590.2  689.98   609.2  700.48
#Mann= 3 , 0 , 0
       0     .07       0     360    .045       0   417.9      .1       0
Bank Sta=360,417.9
XS Rating Curve= 0 ,0
Exp/Cntr=0.3,0.1

Type RM Length L Ch R = 1 ,14560   ,250.7,268.1,285.9
XS GIS Cut Line= 5
     1878250.648      555780.802     1878221.244      555891.955
     1878140.794      556072.054     1878120.503      556250.735
     1878086.064       556329.76
#Sta/Elev= 30
       0  676.38    28.7  667.72    76.6  651.94    95.8  645.98   105.4  643.12
     115  640.86   124.4  639.31   143.2  637.06   227.7   628.3   237.1  627.49
   255.9  626.66   293.4  621.99   321.7  620.67   331.2  619.05   340.6  616.64
   350.1  614.89   359.6  614.28     369   614.2   406.9   614.2   416.3  614.77
   425.8   616.4   444.7  620.63   454.2  623.71   463.7  628.23   473.1  633.66
   492.1  645.34   520.8  666.17     540  678.75   559.1  689.74   578.3  699.83
#Mann= 3 , 0 , 0
       0     .07       0   340.6    .045       0   416.3      .1       0
Bank Sta=340.6,416.3
XS Rating Curve= 0 ,0
Exp/Cntr=0.3,0.1

Type RM Length L Ch R = 1 ,14291.9 ,227.9,230.9,233.6
XS GIS Cut Line= 2
     1878218.009      555751.635     1877803.078      556086.705
#Sta/Elev= 30
       0  678.34    19.4  673.68    29.1  670.57    38.8   666.9      97  642.81
   116.4  635.76   126.1  634.31   155.2  632.15   232.7  627.06   252.1  626.18
   281.2  621.61   300.6  619.58     320  616.77   329.7  615.18   339.4   614.4
   349.1  614.21   358.8   614.3   368.5  615.12   378.2  617.86   387.9  622.37
   397.6  628.94   407.3  637.04     417  645.84   446.1  673.02   455.8  681.02
   465.4  688.02   484.8  699.48   504.2  709.12   513.9  713.17   533.3  719.84
#Mann= 3 , 0 , 0
       0     .07       0     320    .045       0   378.2      .1       0
Bank Sta=320,378.2
XS Rating Curve= 0 ,0
Exp/Cntr=0.3,0.1

Type RM Length L Ch R = 1 ,14061   ,243.6,244.9,246.2
XS GIS Cut Line= 2
     1878129.309      555586.323     1877616.622      555903.893
#Sta/Elev= 30
       0   696.9     9.7  695.36    29.2  691.42    48.6  686.79    58.4  683.88
    68.1  680.31     107  663.98   126.4  657.06   136.2  652.87   165.4  637.14
   175.1  633.41   184.8  632.42   272.4  629.16   282.1  628.56   291.8  626.63
   301.5  623.34   311.3  618.91     321  615.48   330.7  614.32   340.4   614.2
   369.6  614.31   379.4  615.78   389.1  619.79   398.8  625.16   418.3  636.62
   457.2   657.9   505.8  685.25   525.3  695.72   554.4  710.29   603.1  732.57
#Mann= 3 , 0 , 0
       0     .07       0     321    .045       0   379.4      .1       0
Bank Sta=321,379.4
XS Rating Curve= 0 ,0
Exp/Cntr=0.3,0.1

Type RM Length L Ch R = 1 ,13816.1 ,340.4,341.6,342.7
XS GIS Cut Line= 2
     1877997.163      555402.987     1877441.018      555704.404
#Sta/Elev= 30
       0  683.36    19.5  683.34    58.4  681.26    68.1   680.1    77.9  677.84
    87.6  674.36    97.3  669.99   116.8  660.24   126.5  654.93   136.2   648.6
     146  641.35   155.7  635.31   165.4  632.36   204.4  629.59   223.8  628.95
   233.6  628.22   272.5  624.27   282.2  622.26   301.7  615.89   311.4  614.34
   321.2   614.2   369.8   614.5   379.5  616.51   389.3  620.74   428.2  640.79
   476.9  666.82   506.1  683.08   554.7  711.64   564.4  716.82   632.6  749.57
#Mann= 3 , 0 , 0
       0     .07       0   301.7    .045       0   379.5      .1       0
Bank Sta=301.7,379.5
XS Rating Curve= 0 ,0
Exp/Cntr=0.3,0.1

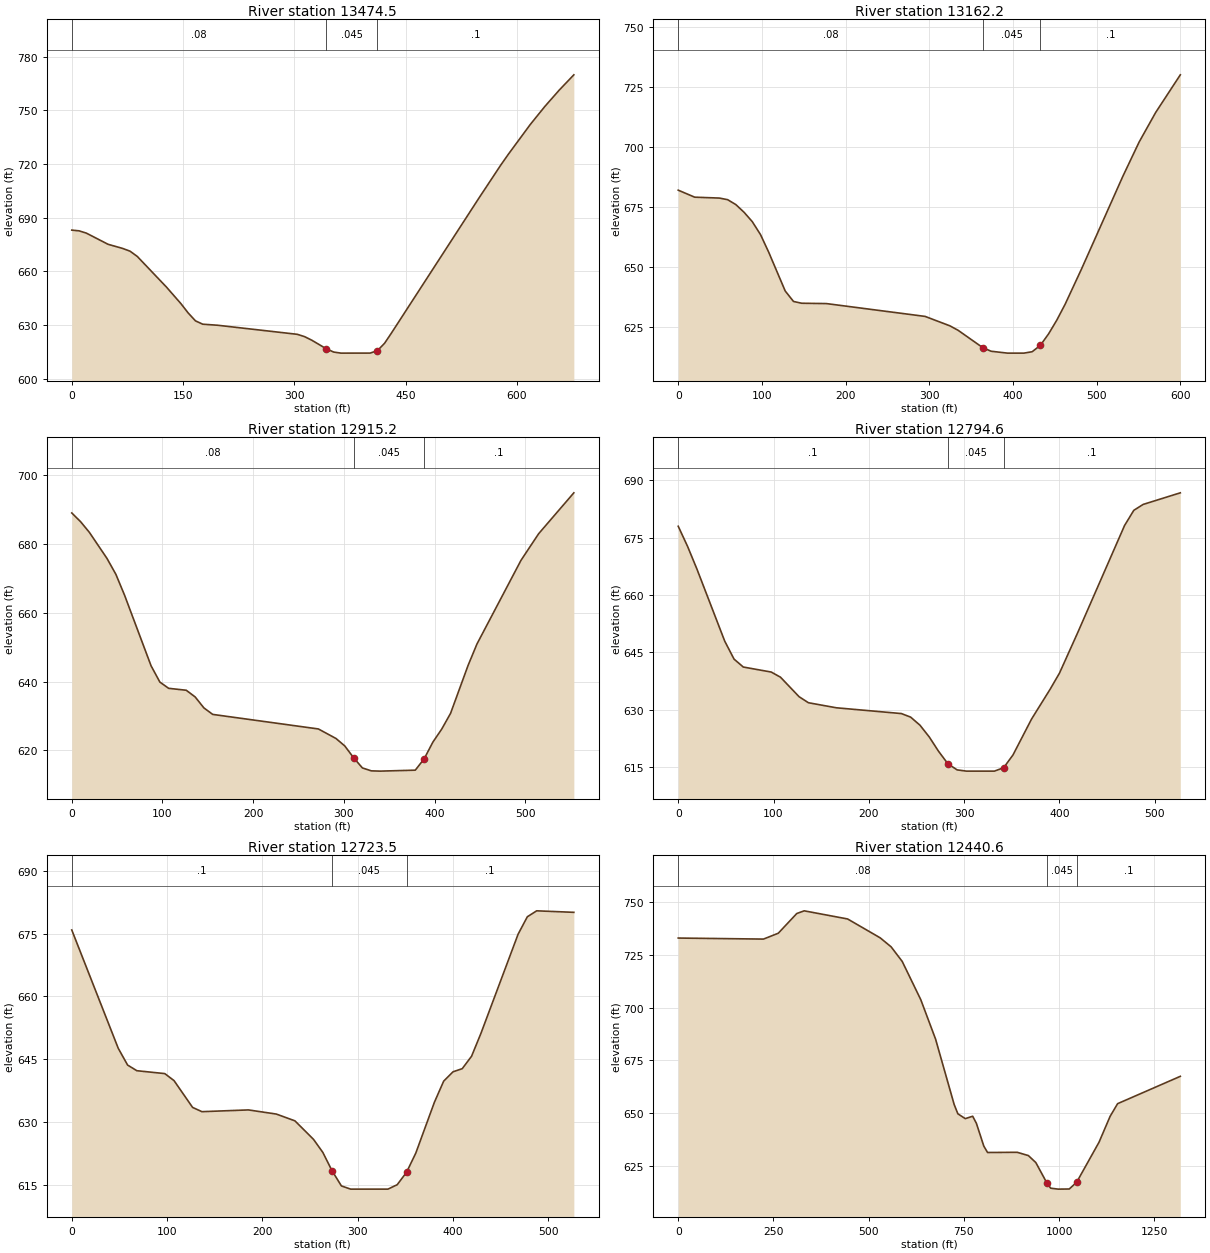
Type RM Length L Ch R = 1 ,13474.5 ,309.4,312.3,315.2
XS GIS Cut Line= 2
     1877873.736      555103.342     1877263.574      555396.028
#Sta/Elev= 30
       0     683     9.8   682.6    19.6  681.33      49  675.06    68.6  672.76
    78.5  671.23    88.3  668.28   127.5   651.2   147.1  641.89   156.9  636.67
   166.7  632.26   176.5  630.38   196.2  629.81     304  624.72   313.8  623.42
   323.6   621.4   343.3  616.58   353.1  614.79   362.9   614.2   402.1  614.22
   411.9  615.54   421.7  619.76   431.5  625.84   549.2  701.19   578.6  719.62
   588.5  725.47   617.9  742.04   637.5  752.11   657.1  761.35   676.7  769.86
#Mann= 3 , 0 , 0
       0     .08       0   343.3    .045       0   411.9      .1       0
Bank Sta=343.3,411.9
XS Rating Curve= 0 ,0
Exp/Cntr=0.3,0.1

Type RM Length L Ch R = 1 ,13162.2 ,245.3,247,248.7
XS GIS Cut Line= 2
     1877798.185      554852.313     1877228.583      555040.282
#Sta/Elev= 30
       0  681.92    19.7     679    49.2  678.63      59  677.96    68.8  675.92
    78.7  672.69    88.5  668.78    98.3   663.4   108.2  655.98   127.8   639.9
   137.7  635.54   147.5  634.79     177  634.65     295   629.3   324.5  625.38
   334.3  623.53   363.8  616.29   373.7  614.79   393.3     614     413     614
   422.8  614.58   432.6  617.23   442.5  622.06   452.3  627.78   462.2  634.38
   481.8  649.08     531  687.58   550.6  701.98   570.3  714.27   599.8     730
#Mann= 3 , 0 , 0
       0     .08       0   363.8    .045       0   432.6      .1       0
Bank Sta=363.8,432.6
XS Rating Curve= 0 ,0
Exp/Cntr=0.3,0.1

Type RM Length L Ch R = 1 ,12915.2 ,120.8,120.5,120.3
XS GIS Cut Line= 2
     1877691.291      554656.382        1877154.      554789.368
#Sta/Elev= 30
       0  689.01     9.7  686.48    19.4  683.38    38.8  675.81    48.6   671.2
    58.3  665.05    87.4  644.62    97.1  639.88   106.8  638.06   126.2   637.5
     136  635.56   145.7  632.36   155.4  630.48   271.9  626.25   291.3  623.48
     301  621.31   310.7  617.89   320.4  614.93   330.2  614.08   339.9     614
   378.7  614.28   388.4  617.54   398.1  622.43   407.8  626.19   417.6  630.79
     437  644.78   446.7  650.94   495.2  675.23   514.7  682.98   553.5  694.86
#Mann= 3 , 0 , 0
       0     .08       0   310.7    .045       0   388.4      .1       0
Bank Sta=310.7,388.4
XS Rating Curve= 0 ,0
Exp/Cntr=0.3,0.1

Type RM Length L Ch R = 1 ,12794.6 ,70.9,71.1,70.9
XS GIS Cut Line= 2
     1877629.916      554543.521     1877120.058      554676.495
#Sta/Elev= 30
       0  677.94     9.8  672.68    19.5  666.84    48.8  647.94    58.6  643.24
    68.3  641.18    97.6  639.87   107.3  638.53   126.8  633.44   136.6  631.86
   165.9  630.54   234.2  629.03   243.9   628.1   253.7  625.99   263.5   622.9
   273.2  619.18     283  615.92   292.7  614.32   302.5     614   331.8     614
   341.5  614.89   351.3  618.22   370.8   627.6   390.3  635.39   400.1  639.59
   419.6  650.37   468.4  678.14   478.1   682.1   487.9  683.64   526.9  686.67
#Mann= 3 , 0 , 0
       0      .1       0     283    .045       0   341.5      .1       0
Bank Sta=283,341.5
XS Rating Curve= 0 ,0
Exp/Cntr=0.3,0.1

Type RM Length L Ch R = 1 ,12723.5 ,284.5,282.9,281.5
XS GIS Cut Line= 2
     1877614.794      554474.528     1877104.936      554607.502
#Sta/Elev= 30
       0  675.87    48.8  647.61    58.6  643.62    68.3  642.27    97.6  641.58
   107.3  639.91   126.8  633.51   136.6  632.49   185.4  632.91   214.7  631.92
   234.2   630.3   253.7  625.88   263.5  622.76   273.2  618.35     283  614.76
   292.7     614   331.8     614   341.5  615.05   351.3  618.01     361  622.58
   380.6  634.76   390.3  639.78   400.1  642.01   409.8  642.76   419.6  645.74
   429.3  651.13   468.4  674.86   478.1  679.02   487.9  680.44   526.9  680.08
#Mann= 3 , 0 , 0
       0      .1       0   273.2    .045       0   351.3      .1       0
Bank Sta=273.2,351.3
XS Rating Curve= 0 ,0
Exp/Cntr=0.3,0.1

Type RM Length L Ch R = 1 ,12440.6 ,303.5,295.2,286.9
XS GIS Cut Line= 6
     1878229.868      554256.556     1877899.312      554244.056
     1877682.645      554216.278     1877468.756      554203.778
     1877079.868      554332.945     1876959.034        554413.5
#Sta/Elev= 30
       0  733.04   223.8  732.55   262.7  735.32   311.3  744.67   330.8  745.95
   444.8  742.09   530.2  733.16     559  728.88   588.2  721.96   636.9  703.84
   675.8  685.13   724.5   654.2   734.3  649.72   753.8  647.42   773.2  648.56
     783   645.2   802.5  634.39   812.3  631.37   890.3  631.46   919.6   629.9
   939.1  626.59   968.4  616.81   978.1  614.45   997.6     614  1026.9  614.06
  1046.4   617.3    1105  636.22  1134.2  648.52  1153.8  654.51  1318.5  667.48
#Mann= 3 , 0 , 0
       0     .08       0   968.4    .045       0  1046.4      .1       0
Bank Sta=968.4,1046.4
XS Rating Curve= 0 ,0
Exp/Cntr=0.3,0.1