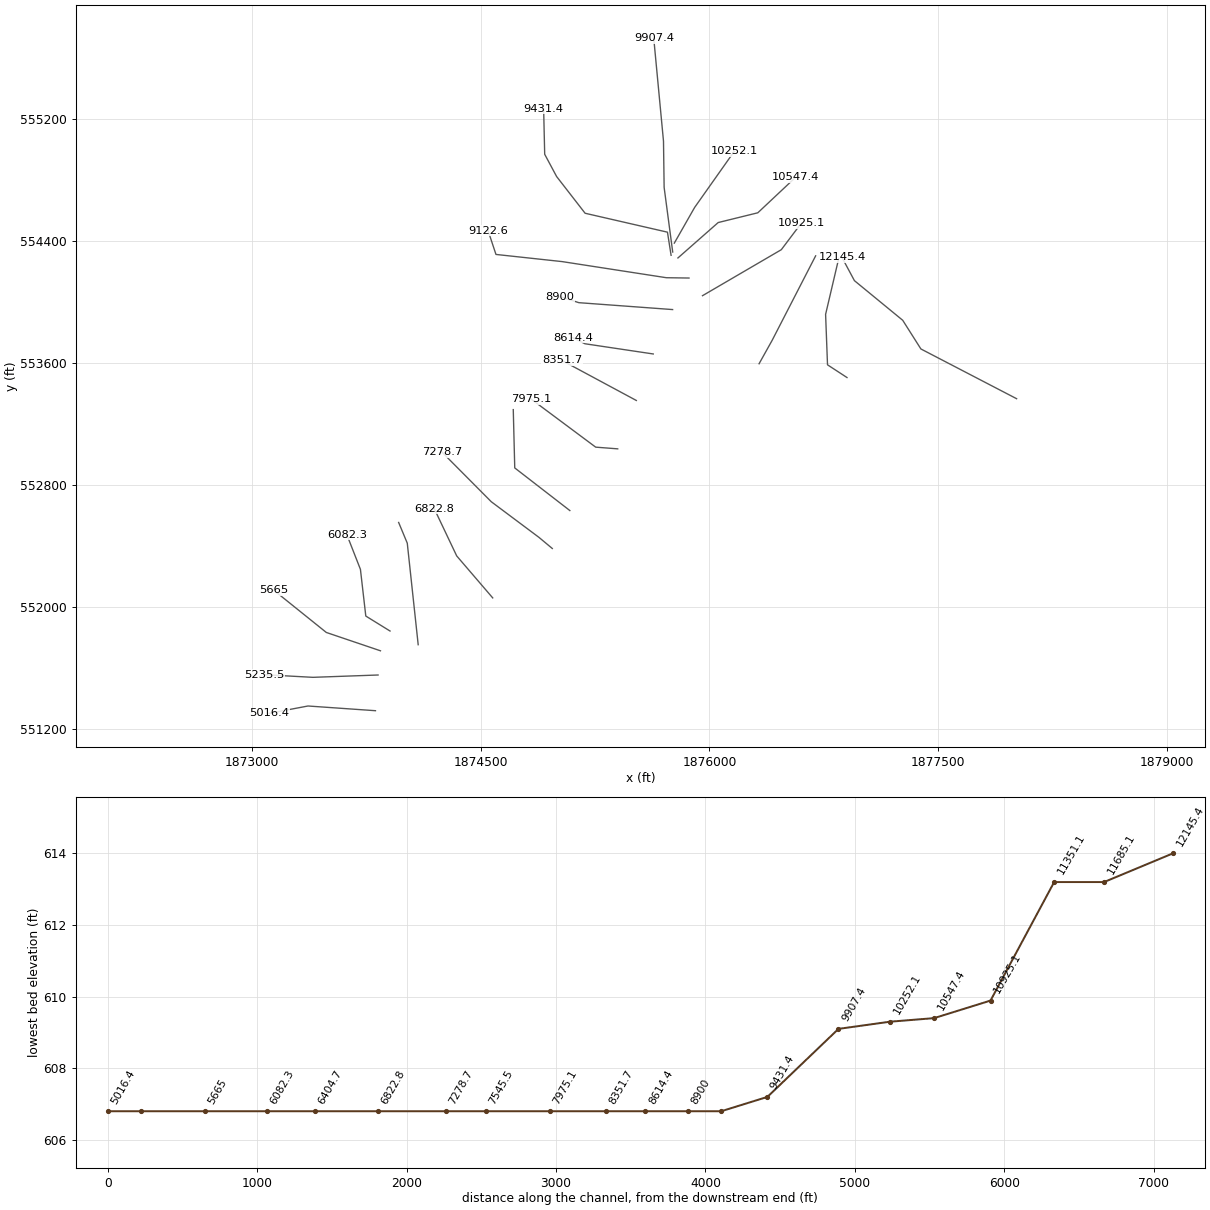
HEC-RAS study BIGSANDYCR.prj: BIGSANDYCR

--- BIGSANDYCR.g01 (geometry) --- (continued)

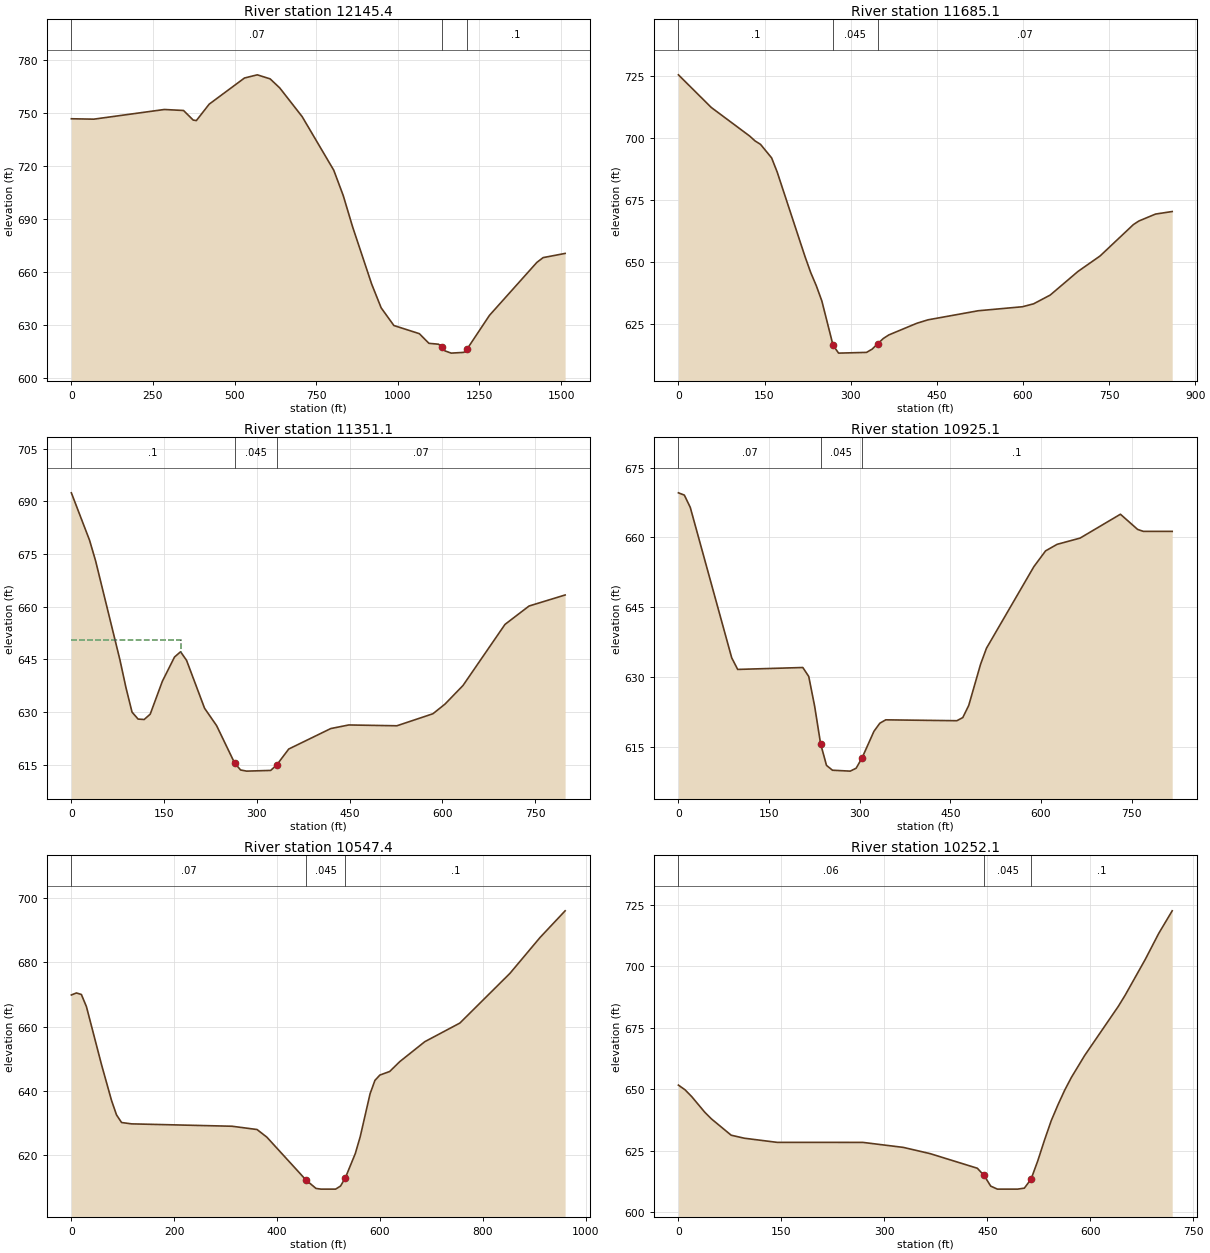
Type RM Length L Ch R = 1 ,12145.4 ,479.6,460.3,441
XS GIS Cut Line= 5
     1878014.029      553365.484      1877386.64      553691.268
      1877267.45      553879.125     1876950.783      554138.847
     1876868.839      554291.625
#Sta/Elev= 30
       0  746.83    68.7   746.6   284.7  752.08   343.6  751.52   373.1  746.09
   382.9   745.8   422.2  755.11   530.2  769.92   569.5  771.73   608.8  769.44
   638.2  764.32   706.9  748.04   803.7  717.66   832.7  703.32   861.7  685.41
   919.7  653.18   948.9  639.66   987.9  629.64  1065.9  625.02  1095.2  619.55
  1124.4  619.06  1134.2  617.69  1143.9   615.3  1163.4     614  1202.4  614.43
  1212.2  616.36  1280.5  635.38  1425.6  665.39  1444.9  668.13  1512.3  670.51
#Mann= 3 , 0 , 0
       0     .07       0  1134.2    .045       0  1212.2      .1       0
Bank Sta=1134.2,1212.2
XS Rating Curve= 0 ,0
Exp/Cntr=0.3,0.1

Type RM Length L Ch R = 1 ,11685.1 ,345.9,334.1,322.9
XS GIS Cut Line= 4
     1876902.172      553504.125     1876774.394      553587.459
     1876761.894      553918.014     1876848.005      554284.681
#Sta/Elev= 30
       0  725.35    57.2   712.2     124  700.69   133.5  698.71     143  697.33
   162.3  691.88     172  686.18   220.6  652.02   230.4  645.68   240.1  640.38
   249.8  634.22   269.3  616.37     279   613.2   327.7   613.5   337.4  614.81
   347.1  616.99   356.9  619.11   366.6  620.55   415.2  625.23   434.7  626.62
     522  630.27   599.2  631.89   618.6  633.07   647.5  636.59   695.8   646.1
   734.4  652.35   792.4     665     802  666.45     831  669.24     860  670.26
#Mann= 3 , 0 , 0
       0      .1       0   269.3    .045       0   347.1     .07       0
Bank Sta=269.3,347.1
XS Rating Curve= 0 ,0
Exp/Cntr=0.3,0.1

Type RM Length L Ch R = 1 ,11351.1 ,438.5,426,412.7
XS GIS Cut Line= 3
     1876325.783      553594.403     1876411.894       553748.57
     1876696.616      554301.347
#Sta/Elev= 30
       0  692.42    29.4  678.94    39.2  673.06    78.5  644.91    88.3  636.97
    98.1  630.01   107.9  628.02   117.7  627.89   127.5  629.41   147.2   638.8
   166.8  645.68   176.6  647.18   186.3  644.73   215.4   631.1   234.9  626.14
     264   615.5   273.7  613.52   283.5   613.2   322.3   613.4     332  614.94
   351.5  619.49   419.5  625.32   448.6  626.34   526.4  626.11   584.6  629.53
   604.1  632.27   633.2  637.56   701.2  654.97   740.1   660.2   798.4  663.34
#Mann= 3 , 0 , 0
       0      .1       0     264    .045       0     332     .07       0
#XS Ineff= 2 , 0
          178.02  650.55
Permanent Ineff=
       F       F
Bank Sta=264,332
XS Rating Curve= 0 ,0
Exp/Cntr=0.3,0.1

Type RM Length L Ch R = 1 ,10925.1 ,384.1,377.7,371.2
XS GIS Cut Line= 3
      1875954.95      554040.236     1876471.616      554341.625
     1876603.561      554516.625
#Sta/Elev= 30
       0  669.57     9.8  669.08    19.6  666.45    88.2  634.19    98.1   631.7
   205.9  632.11   215.7  630.19   225.5   623.8   235.3  615.78   245.1  611.12
     255  610.08   284.4  609.89   294.2  610.52     304  612.74   323.6  618.42
   333.4  620.17   343.2  620.89   460.9   620.7   470.7  621.38   480.5  623.97
   500.1   632.8   509.9  636.25   588.3  653.73   607.7  657.12   626.7  658.52
   664.8  659.86   731.6  664.98   760.1  661.72   769.7   661.3   817.3   661.3
#Mann= 3 , 0 , 0
       0     .07       0   235.3    .045       0     304      .1       0
Bank Sta=235.3,304
XS Rating Curve= 0 ,0
Exp/Cntr=0.3,0.1

Type RM Length L Ch R = 1 ,10547.4 ,279.2,295.3,311.4
XS GIS Cut Line= 4
     1875793.839      554287.459     1876057.728      554519.403
      1876317.45      554583.292     1876566.061      554816.625
#Sta/Elev= 30
       0  669.82     9.8  670.45    19.5  669.98    29.3   666.2    58.6  648.17
    78.1  636.99    87.8   632.5    97.6  630.13   117.1  629.71   312.3  628.97
   360.9  627.95     380  625.58   456.4  612.19   475.5  609.62   485.1   609.4
   513.7   609.4   523.3  610.37   532.8     613   551.9  620.45   561.5  625.71
   580.6  639.04   590.1  643.24   599.7   644.9   618.8  646.01   638.3  649.07
     687  655.28   755.2  661.08   852.6  676.56     911   687.7   959.8  696.01
#Mann= 3 , 0 , 0
       0     .07       0   456.4    .045       0   532.8      .1       0
Bank Sta=456.4,532.8
XS Rating Curve= 0 ,0
Exp/Cntr=0.3,0.1

Type RM Length L Ch R = 1 ,10252.1 ,330.4,344.7,359
XS GIS Cut Line= 3
     1875770.116      554384.681     1875903.246      554618.222
     1876163.079      554985.792
#Sta/Elev= 30
       0   651.6     9.6   649.7    19.2  646.97    38.4  640.56      48  637.88
    76.8  631.23      96     630     144  628.31   268.8   628.3   327.5  626.27
   366.7  623.72   435.2   617.8     445  614.89   454.8  610.51   464.5   609.3
   493.9   609.3   503.7   609.7   513.5  613.36   523.2  620.76     533   629.2
   542.8   637.1   552.6  643.55   562.4  649.51   572.2  654.73   591.7  663.72
   640.7   683.7   650.5  688.17   679.8  702.74   699.4   713.3     719  722.48
#Mann= 3 , 0 , 0
       0     .06       0     445    .045       0   513.5      .1       0
Bank Sta=445,513.5
XS Rating Curve= 0 ,0
Exp/Cntr=0.3,0.1

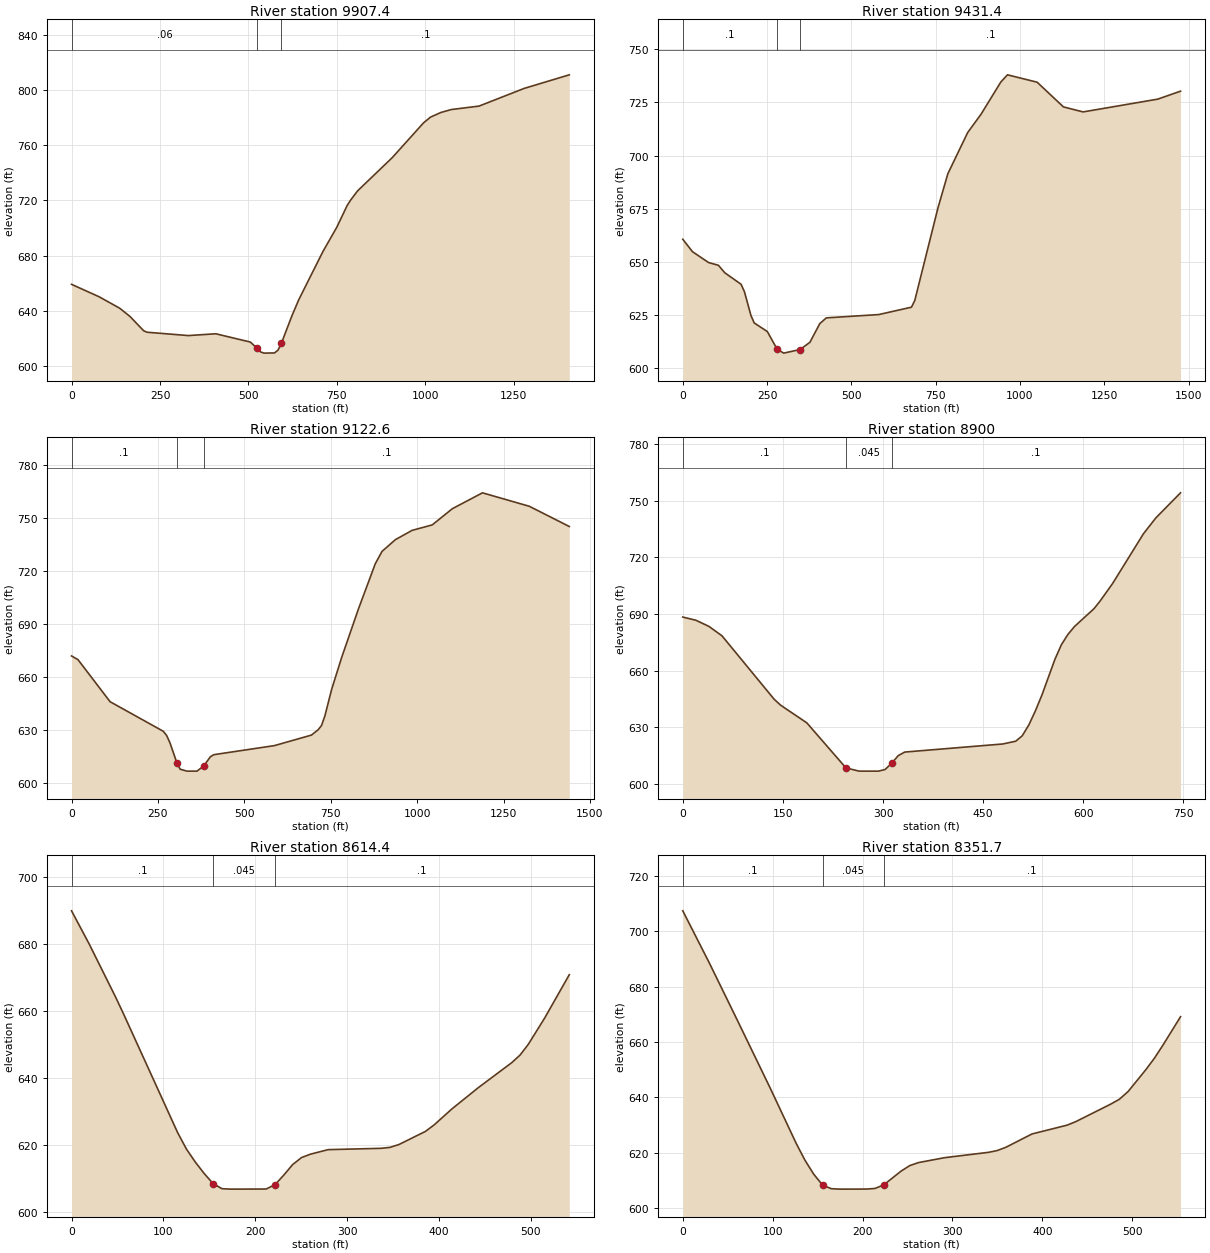
Type RM Length L Ch R = 1 ,9907.4  ,445.8,476,506.1
XS GIS Cut Line= 4
     1875759.561      554326.347     1875703.357      554749.681
      1875699.19      555052.459     1875635.302       555726.07
#Sta/Elev= 30
       0  659.07    77.6  650.07   135.9  641.75     165  635.77   203.8  625.34
   213.5  624.27     330  621.85   407.6  623.15   505.2  617.14   524.7  612.54
   534.5  609.92   544.3   609.1   573.6  609.25   583.3  611.24   593.1  616.32
   622.4  636.03   641.9  647.79   710.3  682.88   749.5  700.52   778.9  716.36
   788.7  720.28   808.3  726.96   906.4  751.13   994.6  776.34  1014.2  780.49
  1043.7  783.89  1073.1  786.01  1151.5  788.52    1279  801.37  1406.5  811.23
#Mann= 3 , 0 , 0
       0     .06       0   524.7    .045       0   593.1      .1       0
Bank Sta=524.7,593.1
XS Rating Curve= 0 ,0
Exp/Cntr=0.3,0.1

Type RM Length L Ch R = 1 ,9431.4  ,307.1,308.8,310.5
XS GIS Cut Line= 6
     1875749.005      554304.681     1875725.116      554456.347
     1875185.302      554580.236     1874998.496      554820.861
     1874920.371      554966.695     1874913.427      555265.306
#Sta/Elev= 30
       0   660.7    28.8  654.86    76.8  649.74   105.6  648.48   124.8  644.93
     173  639.54   182.7  636.11   202.1   624.9   211.8  621.39   250.7  617.34
   279.8  609.06   299.3   607.2   347.9   608.9     377  612.29   406.2  621.04
   425.6  623.76   581.1  625.32   678.2  628.79     688  631.93   756.5   675.3
     786  691.47     845  710.88   884.3  719.41   943.2  734.59   962.9  737.97
  1050.9   734.5  1128.8   722.9  1187.1  720.54  1408.7  726.55  1476.1  730.29
#Mann= 3 , 0 , 0
       0      .1       0   279.8    .045       0   347.9      .1       0
Bank Sta=279.8,347.9
XS Rating Curve= 0 ,0
Exp/Cntr=0.3,0.1

Type RM Length L Ch R = 1 ,9122.6  ,220.8,222.6,224.4
XS GIS Cut Line= 5
     1875866.552      554155.931      1875717.94      554158.014
     1875034.607       554263.57     1874600.927      554310.445
     1874549.274      554466.036
#Sta/Elev= 30
       0  671.85    18.6  669.79   111.5  646.02   265.5   629.3   275.2  626.94
     285  622.68   304.4  611.66   314.2   607.9   333.7   606.8   362.9   606.8
   382.4  609.71   401.8  614.93   411.6  616.09   586.9  621.21     694  627.15
   713.5  630.16   723.2  632.56   732.9   637.9   752.4  652.87   781.6  671.04
   830.3  698.52   878.8  723.94   898.2   730.9     937  737.57   985.5  742.82
  1043.6  745.89  1101.8  755.05    1189  764.02  1324.5  756.42  1440.2     745
#Mann= 3 , 0 , 0
       0      .1       0   304.4    .045       0   382.4      .1       0
Bank Sta=304.4,382.4
XS Rating Curve= 0 ,0
Exp/Cntr=0.3,0.1

Type RM Length L Ch R = 1 ,8900    ,287.3,285.6,283.9
XS GIS Cut Line= 3
     1875758.913      553949.334     1875144.329      553994.472
     1875021.065      554034.403
#Sta/Elev= 30
       0   688.4    19.6  686.72    39.1  683.47    58.7  678.48   136.9  644.88
   146.7   641.7   185.8  632.39   244.5   608.5   264.1   606.8   293.4   606.8
   303.2  607.68     313  610.96   322.8     615   332.6   616.9   479.3  621.17
   498.9  622.65   508.6  625.51   518.4  631.19   528.2  638.61     538     647
   557.6  666.02   567.3  673.77   577.1  679.21   586.9  683.38   616.2  692.86
   625.5  696.98     644  706.16   690.3  732.55   708.8  740.91   745.8   754.2
#Mann= 3 , 0 , 0
       0      .1       0   244.5    .045       0     313      .1       0
Bank Sta=244.5,313
XS Rating Curve= 0 ,0
Exp/Cntr=0.3,0.1

Type RM Length L Ch R = 1 ,8614.4  ,270.4,262.7,254.8
XS GIS Cut Line= 3
     1875632.084      553658.501      1875184.26      553725.375
     1875104.399      553765.306
#Sta/Elev= 30
       0  689.99    19.3  680.03    48.2  664.08    57.8  658.47   115.6  623.66
   125.2  618.74   134.9  614.85   144.5  611.45   154.1  608.46   163.8  606.93
   173.4   606.8   211.9  606.83   221.6  608.12   231.2     611   240.8  614.14
   250.5  616.24   260.1  617.24   279.4   618.6   337.2     619   346.8  619.28
   356.4  620.11   385.4  624.05     395  626.02   414.2  630.76   443.2  637.17
   479.6  644.64   488.5  646.88   497.4  650.06   515.3  657.95   542.1   670.9
#Mann= 3 , 0 , 0
       0      .1       0   154.1    .045       0   221.6      .1       0
Bank Sta=154.1,221.6
XS Rating Curve= 0 ,0
Exp/Cntr=0.3,0.1

Type RM Length L Ch R = 1 ,8351.7  ,379.9,376.6,373.3
XS GIS Cut Line= 2
     1875521.065      553353.847     1875033.218         553616.
#Sta/Elev= 30
       0  707.42    29.2  688.79    58.3  669.47    97.2  643.38   126.3  623.26
     136  617.22   145.7   612.2   155.5  608.27   165.2  606.95   174.9   606.8
     204  606.82   213.8  607.04   223.5   608.3   242.9  613.32   252.6  615.31
   262.3   616.4   291.5  618.18   340.1   620.1   349.8  620.74   359.5  621.93
   388.6  626.75   427.5  629.92   437.2  631.19   476.1  637.53   485.8   639.3
   495.5   642.1     515   649.9   524.7  654.11   534.4  658.94   553.8  669.14
#Mann= 3 , 0 , 0
       0      .1       0   155.5    .045       0   223.5      .1       0
Bank Sta=155.5,223.5
XS Rating Curve= 0 ,0
Exp/Cntr=0.3,0.1

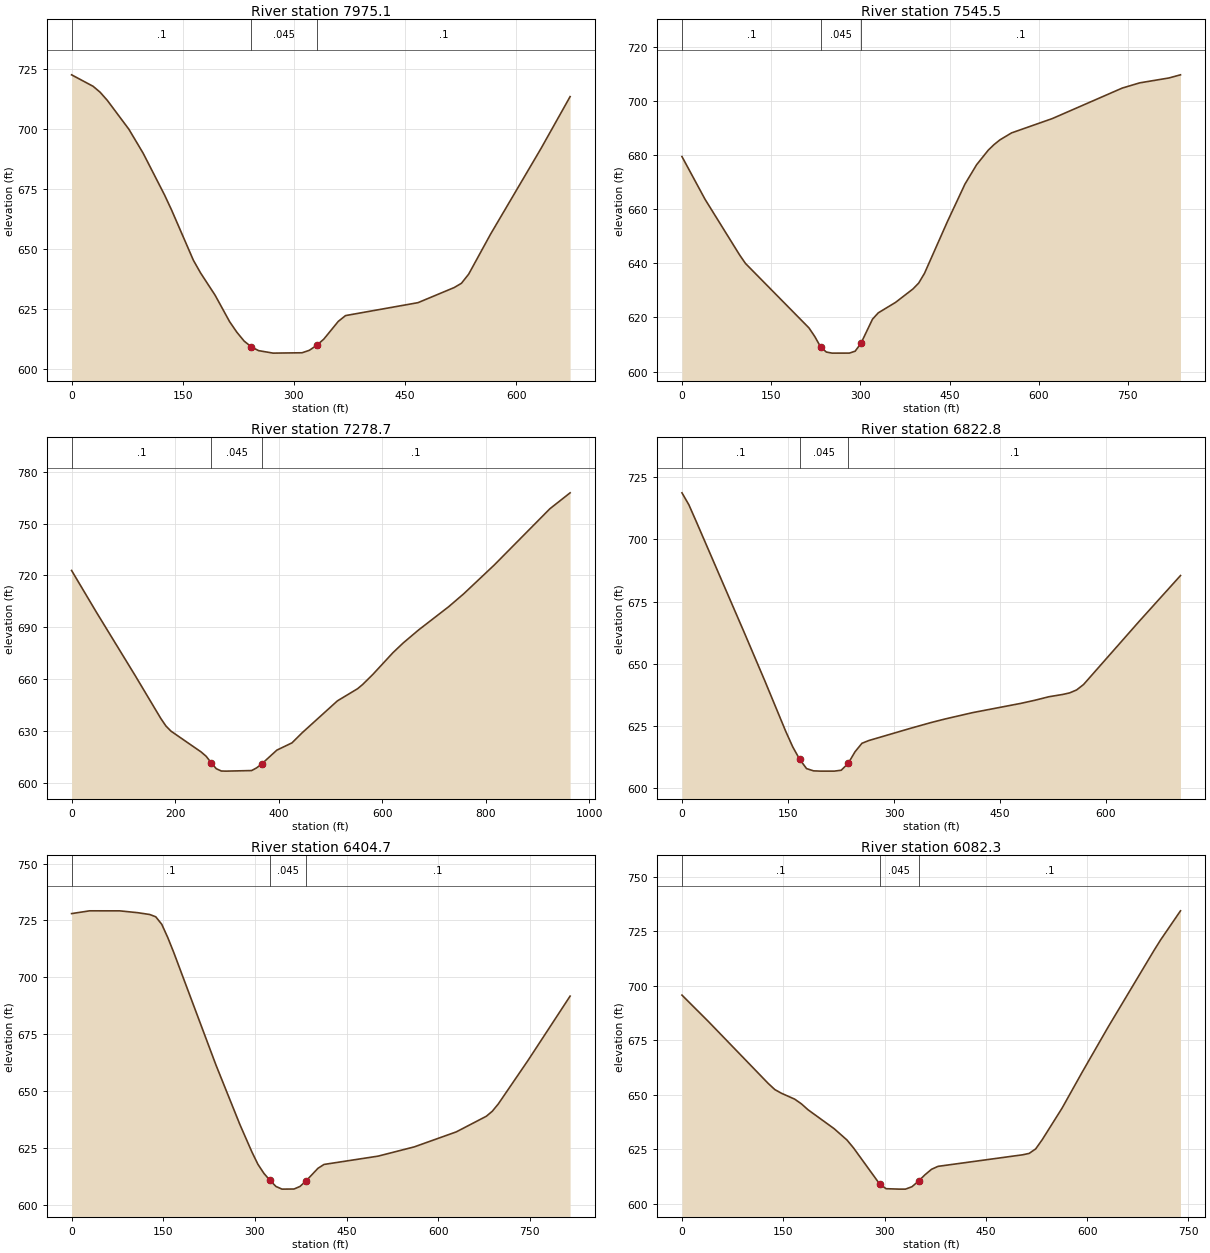
Type RM Length L Ch R = 1 ,7975.1  ,430,429.6,429.2
XS GIS Cut Line= 3
     1875399.082      553036.992     1875254.638      553048.103
     1874831.026      553363.381
#Sta/Elev= 30
       0   722.5      29  717.74    38.6  715.24    48.3  711.85    77.3  699.89
    96.6  689.91   125.6  672.48   135.2  666.14   164.4  645.41   174.2  640.09
   193.8  630.84   213.3  619.88   223.1  615.48   232.9  611.81   242.7  609.38
   252.4  607.84     272   606.8   311.1  606.95   320.9  607.97   330.7  610.01
   340.4  612.61     360     620   369.8  622.41   467.6  627.78   516.5  634.07
   526.2  635.83     536  639.64   565.4  656.19   633.8  691.97   672.9  713.44
#Mann= 3 , 0 , 0
       0      .1       0   242.7    .045       0   330.7      .1       0
Bank Sta=242.7,330.7
XS Rating Curve= 0 ,0
Exp/Cntr=0.3,0.1

Type RM Length L Ch R = 1 ,7545.5  ,266.3,266.8,267.1
XS GIS Cut Line= 3
     1875085.193      552632.825     1874724.082      552911.992
      1874714.36      553293.936
#Sta/Elev= 30
       0  679.44    38.8  663.66    97.1  643.04   106.8  639.95   213.6  616.12
   223.4  612.94   233.1  609.12   242.8   607.2   252.5   606.8   281.6  606.81
   291.3  607.52     301  610.41   320.5  619.36   330.2  621.69   359.3  625.56
   388.5  630.51   398.2   632.7   407.9  636.28   446.7  655.53     476  669.28
   495.6  676.44   515.2  681.82     525  683.89   534.8  685.62   554.4   688.2
     623   693.5   740.5  704.76   769.9  706.69   818.9  708.49   838.5  709.66
#Mann= 3 , 0 , 0
       0      .1       0   233.1    .045       0     301      .1       0
Bank Sta=233.1,301
XS Rating Curve= 0 ,0
Exp/Cntr=0.3,0.1

Type RM Length L Ch R = 1 ,7278.7  ,460.9,455.9,450.9
XS GIS Cut Line= 4
     1874970.263      552384.214     1874882.763      552457.131
     1874570.263      552690.464     1874246.304      553016.158
#Sta/Elev= 30
       0  722.84    47.5  698.93   123.6  661.71   172.4  637.26   182.2  632.94
   191.9  629.96   250.4  617.87   260.2  615.33   269.9  611.57   279.6   608.2
   289.4  606.86   299.2   606.8   347.9  607.13   357.6   608.7   367.4  610.96
   396.6  618.94   425.9  623.15   445.4  628.94   513.7  647.44   552.8  654.49
   562.5  656.93   582.1  662.72   621.2  675.37   640.7   680.9   670.1  688.34
   728.7   701.9     758  709.43   816.7     726   924.2  758.53   963.3  767.75
#Mann= 3 , 0 , 0
       0      .1       0   269.9    .045       0   367.4      .1       0
Bank Sta=269.9,367.4
XS Rating Curve= 0 ,0
Exp/Cntr=0.3,0.1

Type RM Length L Ch R = 1 ,6822.8  ,431.6,418,404.4
XS GIS Cut Line= 3
     1874579.638      552060.603     1874343.526      552335.603
     1874196.304      552645.325
#Sta/Elev= 30
       0   718.7     9.8  713.87    19.6  707.56    88.2  662.48   117.6  642.86
   146.9  622.75   156.7  616.58   166.5  611.56   176.3  607.82   186.1  606.91
   195.9   606.8   215.5   606.8   225.3  607.15   235.1  609.87   244.9  614.59
   254.7     618   264.5  619.11   323.3  624.01   352.7  626.35   372.2  627.76
   411.4  630.33     480  634.07   499.6  635.31   519.2  636.71   538.8  637.63
   548.6  638.26   558.4  639.44   568.2  641.61   646.6  666.91   705.4  685.43
#Mann= 3 , 0 , 0
       0      .1       0   166.5    .045       0   235.1      .1       0
Bank Sta=166.5,235.1
XS Rating Curve= 0 ,0
Exp/Cntr=0.3,0.1

Type RM Length L Ch R = 1 ,6404.7  ,322.3,322.4,322.6
XS GIS Cut Line= 3
     1874091.085      551754.046     1874019.494      552419.087
     1873962.975      552554.733
#Sta/Elev= 30
       0  728.02    29.5  729.24    78.7  729.23   108.2  728.42   127.9  727.62
   137.7  726.62   147.6   723.3   157.4  717.48   167.2  710.92   236.1  661.51
   275.4  635.23   295.1  623.14   304.9  617.74   314.8  613.71   324.6  610.68
   334.4  607.98   344.3   606.8     364  606.85   373.8  607.98   383.6   610.4
   403.3  615.99   413.1  617.66   501.7  621.32   560.7  625.38   629.5  631.98
   678.7  638.86   688.5  641.08   698.3  644.28   747.3  663.58   815.8  691.72
#Mann= 3 , 0 , 0
       0      .1       0   324.6    .045       0   383.6      .1       0
Bank Sta=324.6,383.6
XS Rating Curve= 0 ,0
Exp/Cntr=0.3,0.1

Type RM Length L Ch R = 1 ,6082.3  ,399.6,417.3,434.9
XS GIS Cut Line= 4
     1873906.446      551843.618     1873747.592      551941.708
     1873712.406      552247.646     1873623.461      552474.508
#Sta/Elev= 30
       0  695.74    39.3  683.59   127.7  655.26   137.6  652.42   147.4  650.74
     167  648.04   176.9  645.89   186.7  643.18   225.2  634.55   244.4  629.31
   254.1  625.68   292.6  609.22   302.2     607   321.4   606.8     331   606.8
   340.7  607.92   350.3  610.47   359.9  613.38   369.6  615.89   379.2  617.24
   504.4  622.53   514.2  623.18   523.9  625.26   533.6   629.5   562.9  643.91
   592.1  660.08   631.1  681.08   699.3  716.34   709.1  721.17   738.3  734.38
#Mann= 3 , 0 , 0
       0      .1       0   292.6    .045       0   350.3      .1       0
Bank Sta=292.6,350.3
XS Rating Curve= 0 ,0
Exp/Cntr=0.3,0.1

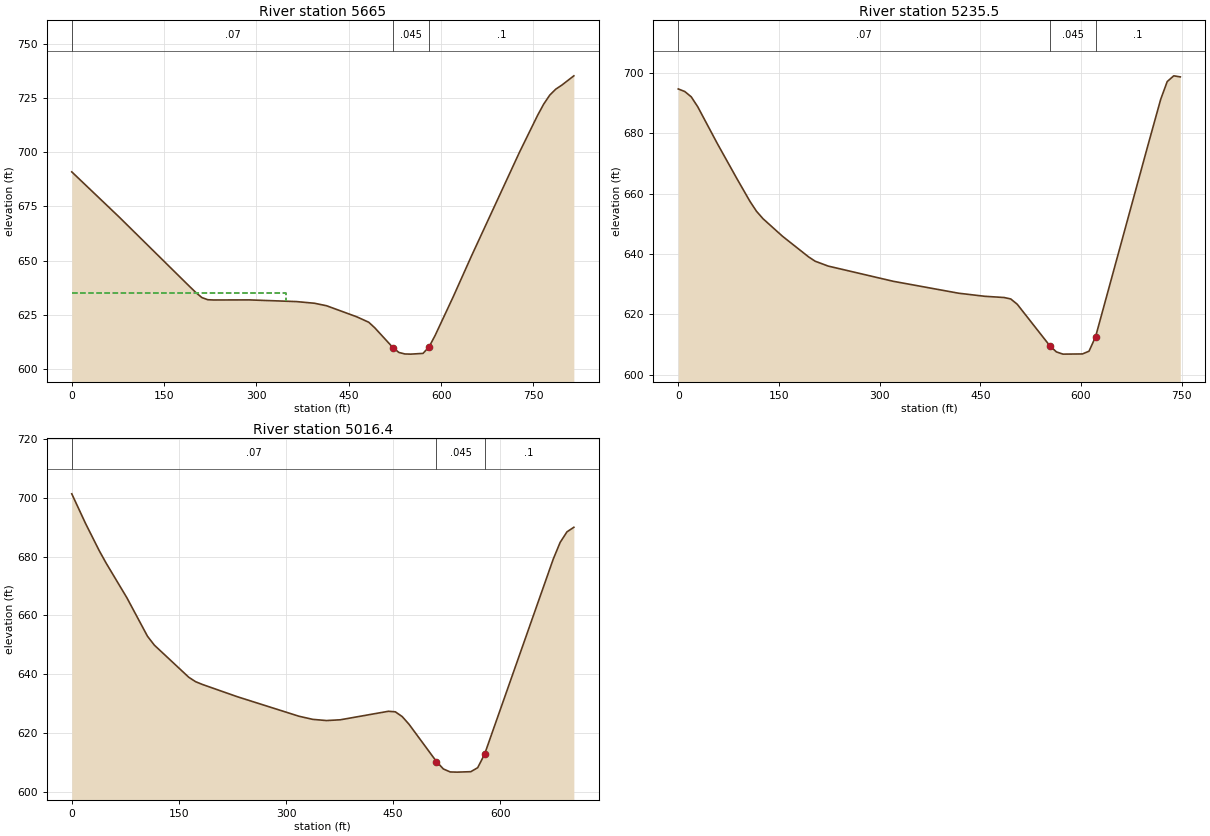
Type RM Length L Ch R = 1 ,5665    ,415.4,429.6,443.4
XS GIS Cut Line= 3
     1873843.772      551714.104     1873488.853      551834.185
     1873145.103      552110.227
#Sta/Elev= 30
       0  690.92    76.9   670.1   192.1  637.83   201.8  635.18   211.4   632.9
     221  631.91   230.6  631.79   288.2  631.83   365.1  631.05   394.3  630.28
   413.9  629.13   462.9  624.03   482.4  621.52   492.2  618.96   521.6  609.85
   531.4  607.57   541.2  606.87     551   606.8   570.6  607.14   580.4  610.14
   590.2  615.39   619.6  633.24     649   651.9   727.4  700.05   756.8  717.06
   766.6  722.18   776.4  726.32   786.2  729.09     796  730.94   815.6  735.25
#Mann= 3 , 0 , 0
       0     .07       0   521.6    .045       0   580.4      .1       0
#XS Ineff= 2 , 0
          347.99  634.81
Permanent Ineff=
       F       F
Bank Sta=521.6,580.4
XS Rating Curve= 0 ,0
Exp/Cntr=0.3,0.1

Type RM Length L Ch R = 1 ,5235.5  ,213.6,219.1,224.5
XS GIS Cut Line= 3
     1873828.066      551555.574     1873400.983      551540.296
     1873080.844      551557.657
#Sta/Elev= 30
       0  694.68     9.7  693.84    19.4  692.06    29.1  688.76    58.3  676.56
    87.4  664.96   106.8  657.45   116.6  654.14   126.3  651.68   155.4  645.85
   194.2  639.03     204  637.59   223.4  635.98   320.5  630.93   417.6  626.99
   456.5  625.97   485.6  625.56   495.4  625.08   505.1  623.32   553.7  609.54
   563.4  607.54   573.1   606.8   602.2  606.86     612  607.78   621.7  612.52
   699.4  675.71   718.8  691.26   728.5  697.13   738.2  699.03     748  698.68
#Mann= 3 , 0 , 0
       0     .07       0   553.7    .045       0   621.7      .1       0
Bank Sta=553.7,621.7
XS Rating Curve= 0 ,0
Exp/Cntr=0.3,0.1

Type RM Length L Ch R = 1 ,5016.4  ,273.8,270.8,267.7
XS GIS Cut Line= 3
     1873810.902      551321.685     1873368.726      551352.518
     1873113.726      551304.185
#Sta/Elev= 30
       0   701.3    19.3  691.23    38.5  681.97    48.2  677.73    77.1  666.03
     106  652.94   115.6  649.92   163.8  639.01   173.4   637.5   183.1  636.55
   231.3  632.44     318  625.78   337.3  624.72   356.5  624.31   375.8  624.57
   443.2  627.46   452.9  627.28   462.5  625.67   472.1  623.05   510.5   610.4
   520.2  607.87   529.8  606.86   539.4   606.8   558.6  606.95   568.2  608.31
   577.8  612.84     674  679.16   683.6  684.79   693.2   688.4   702.8  689.94
#Mann= 3 , 0 , 0
       0     .07       0   510.5    .045       0   577.8      .1       0
Bank Sta=510.5,577.8
XS Rating Curve= 0 ,0
Exp/Cntr=0.3,0.1