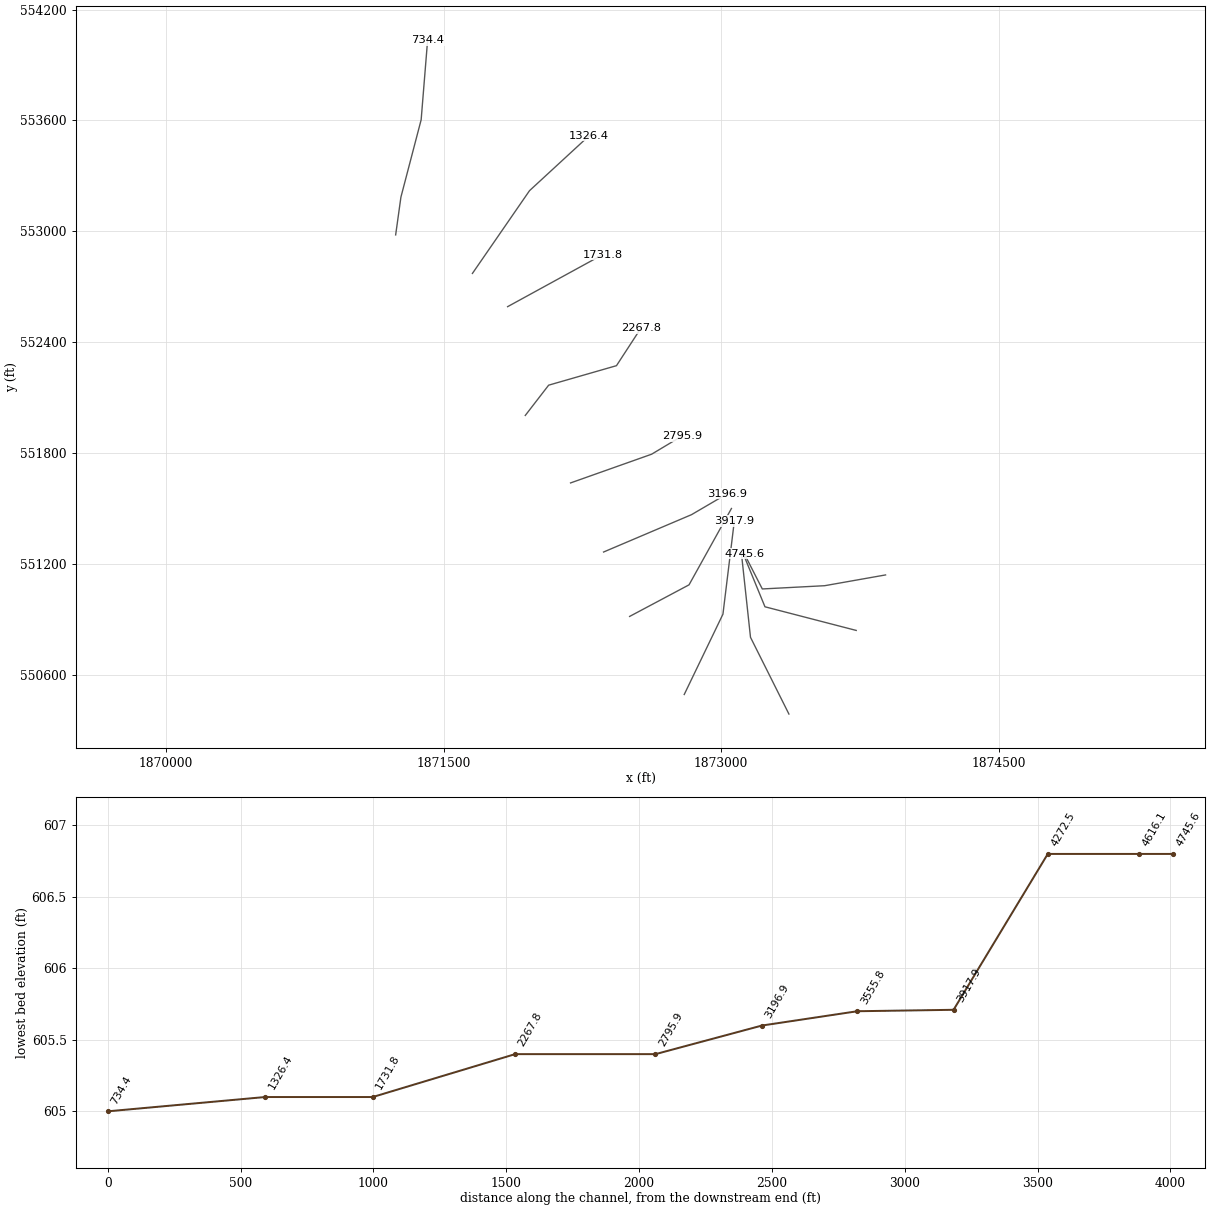
HEC-RAS study BIGSANDYCR.prj: BIGSANDYCR

--- BIGSANDYCR.g01 (geometry) --- (continued)

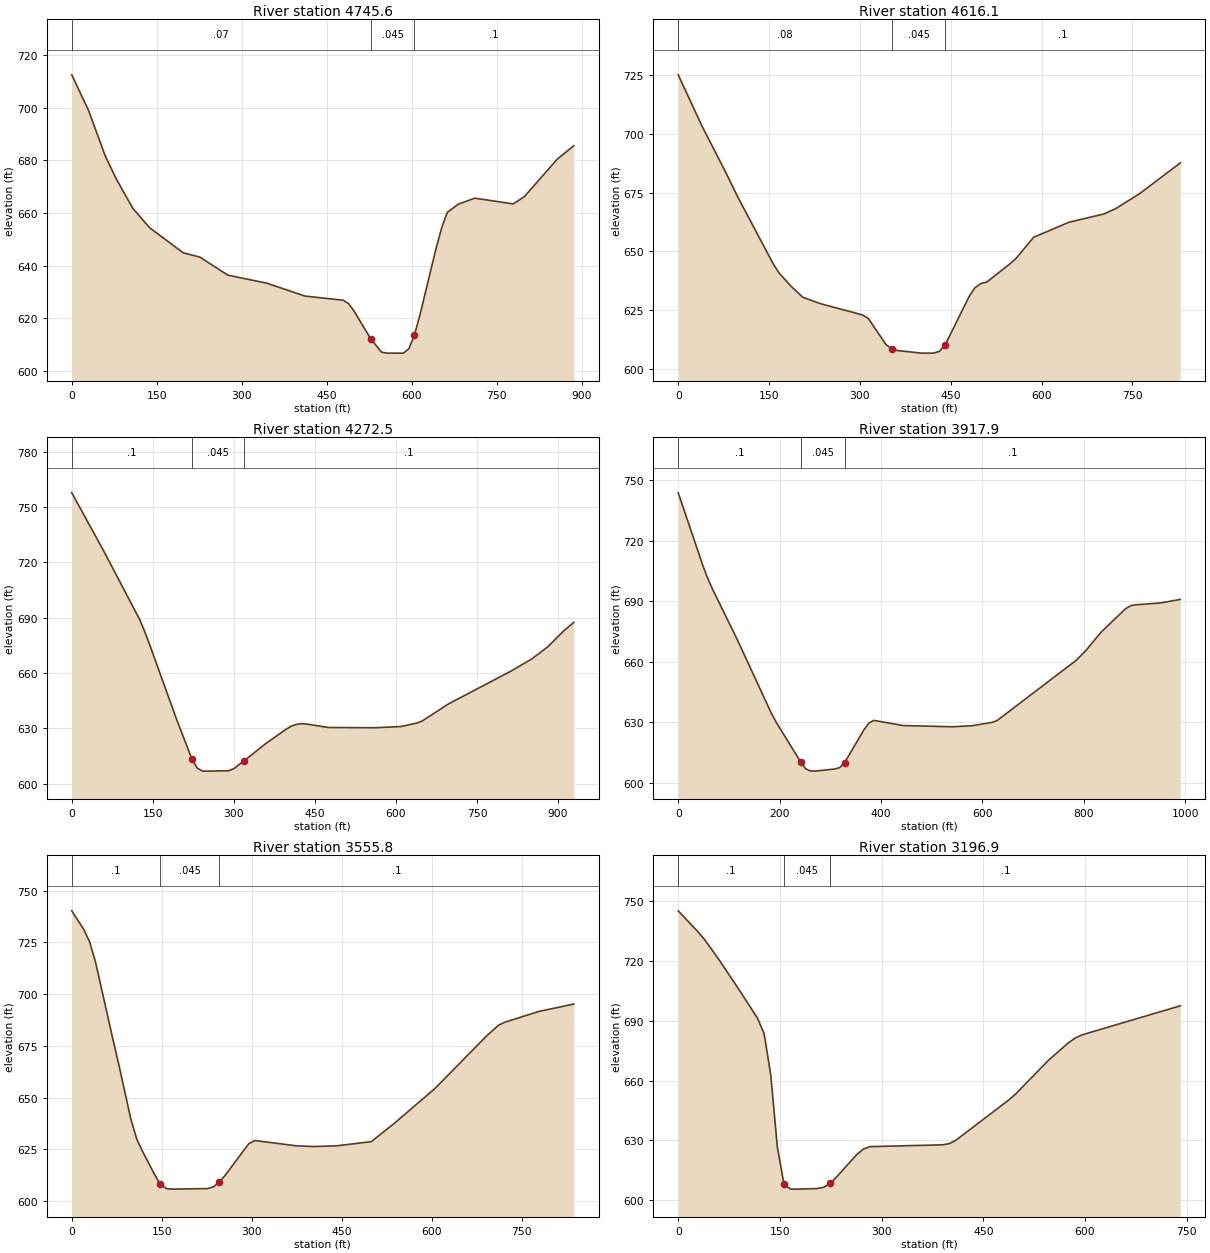
Type RM Length L Ch R = 1 ,4745.6  ,136.5,129.5,122.6
XS GIS Cut Line= 4
      1873889.18      551139.321     1873560.013      551080.987
     1873222.814      551063.383     1873125.489      551253.674
#Sta/Elev= 30
       0  712.54    29.5  699.08      59  681.77    78.7  672.89   108.2  661.66
   137.6   654.4   196.6  644.92   226.1  643.27   275.3  636.43   343.9  633.38
   411.5  628.47     479   626.9   488.6  625.56   498.3  622.66   527.2   612.3
   546.5  607.15   556.2   606.8   585.1   606.8   594.8  608.49   604.4  613.61
   614.1  621.22     643  646.87   652.7  654.51   662.3  660.25   681.7  663.37
   710.8  665.68   778.8   663.5   798.2  666.22   856.5  680.51   885.7  685.61
#Mann= 3 , 0 , 0
       0     .07       0   527.2    .045       0   604.4      .1       0
Bank Sta=527.2,604.4
XS Rating Curve= 0 ,0
Exp/Cntr=0.3,0.1

Type RM Length L Ch R = 1 ,4616.1  ,362.9,343.5,324.2
XS GIS Cut Line= 3
      1873730.54      550838.826     1873237.214      550966.839
     1873116.045      551262.563
#Sta/Elev= 30
       0     725    39.2  703.26    78.4  683.61      98  673.28   156.8  644.75
   166.6  640.82   186.2  635.22   205.8  630.52   235.2  627.78   303.8  623.06
   313.6  621.63     343  610.49   352.8  608.57   362.6  607.87   401.8   606.8
   421.4   606.8   431.2  607.51   441.1  610.44   480.3  630.81   490.1   634.6
   499.9  636.36   509.7     637   548.4  644.84   558.1  647.08   587.1  656.03
   645.2  662.38   703.4  665.93   722.7   668.2   761.5  674.44   829.2   687.6
#Mann= 3 , 0 , 0
       0     .08       0   352.8    .045       0   441.1      .1       0
Bank Sta=352.8,441.1
XS Rating Curve= 0 ,0
Exp/Cntr=0.3,0.1

Type RM Length L Ch R = 1 ,4272.5  ,375.4,354.6,333.4
XS GIS Cut Line= 3
     1873366.749      550386.126      1873159.02      550801.585
     1873109.156      551263.632
#Sta/Elev= 30
       0  757.65    58.1   726.7   125.8   688.9   135.5  682.09   145.2  674.52
   193.5  635.26   222.6  613.16   232.2  608.48   241.9  606.82   251.6   606.8
   290.3  607.02     300  608.16   319.3  612.47     358   621.5   396.8  629.55
   406.4  631.23   416.1  632.15   425.8  632.54   435.5   632.3   474.2  630.46
   561.3  630.31   609.7  630.99   638.8  632.87   648.4  633.94   696.9  643.19
     813  661.04   851.8  667.69   880.8  674.14   909.9  682.68   929.2  687.44
#Mann= 3 , 0 , 0
       0      .1       0   222.6    .045       0   319.3      .1       0
Bank Sta=222.6,319.3
XS Rating Curve= 0 ,0
Exp/Cntr=0.3,0.1

Type RM Length L Ch R = 1 ,3917.9  ,376.4,362.2,347.9
XS GIS Cut Line= 3
     1872800.777      550492.029     1873010.013      550926.821
      1873071.61      551431.265
#Sta/Elev= 30
       0  743.84    48.2  708.06    57.9  701.57    67.6  696.07   115.8  671.35
   183.4  634.63     193  630.08   241.3   610.4   250.9  606.96   260.6   605.8
   270.2  605.71   308.8  606.76   318.5  607.45   328.1  609.83   366.7  626.35
   376.4  629.58     386   630.9   443.9  628.33   541.2  627.72   580.2  628.26
   619.3   629.9   629.1  630.81   785.5  660.75     805  665.76   834.3  674.68
   883.2  686.43     893  687.82   902.8  688.28   951.6  689.17   990.7  690.94
#Mann= 3 , 0 , 0
       0      .1       0   241.3    .045       0   328.1      .1       0
Bank Sta=241.3,328.1
XS Rating Curve= 0 ,0
Exp/Cntr=0.3,0.1

Type RM Length L Ch R = 1 ,3555.8  ,360.9,358.9,357
XS GIS Cut Line= 3
     1872505.544      550914.648     1872826.725      551085.655
     1873055.985      551498.973
#Sta/Elev= 30
       0  740.29    19.7  731.43    29.5  725.48    39.3  715.86    68.8   677.8
    78.7  665.54    98.3  639.76   108.2  629.98     118   623.9   137.7  612.93
   147.5  607.99   157.4  606.01   167.2   605.7   226.2  605.96     236  606.82
   245.9  609.14   255.7  612.45     295  627.69   304.9  629.21   373.5  626.66
   402.4   626.3     441  626.63   498.9  628.65   537.5  637.55     605  654.34
   691.8  679.98   711.1  684.99   720.8  686.35   778.6  691.66   836.5  695.22
#Mann= 3 , 0 , 0
       0      .1       0   147.5    .045       0   245.9      .1       0
Bank Sta=147.5,245.9
XS Rating Curve= 0 ,0
Exp/Cntr=0.3,0.1

Type RM Length L Ch R = 1 ,3196.9  ,402.3,401,399.6
XS GIS Cut Line= 3
     1872364.725      551263.348     1872840.156      551465.603
     1873033.416      551578.835
#Sta/Elev= 30
       0     745    29.2  734.45      39  730.55    58.5  721.33    87.7  706.54
     117  691.19   126.7  683.48   136.5  662.73   146.2   626.7     156  607.99
   165.7  605.62   175.5   605.6   204.7  605.89   214.5   606.5   224.2  608.44
     234  611.85   263.2  622.88     273  625.64   282.7  626.89   389.9  627.79
   399.7  628.39   409.4  630.05   487.4   650.2   497.2   653.1   545.9  670.06
   575.1  678.77   584.8  681.14   594.6  682.71   604.3  683.75   740.6  697.42
#Mann= 3 , 0 , 0
       0      .1       0     156    .045       0   224.2      .1       0
Bank Sta=156,224.2
XS Rating Curve= 0 ,0
Exp/Cntr=0.3,0.1

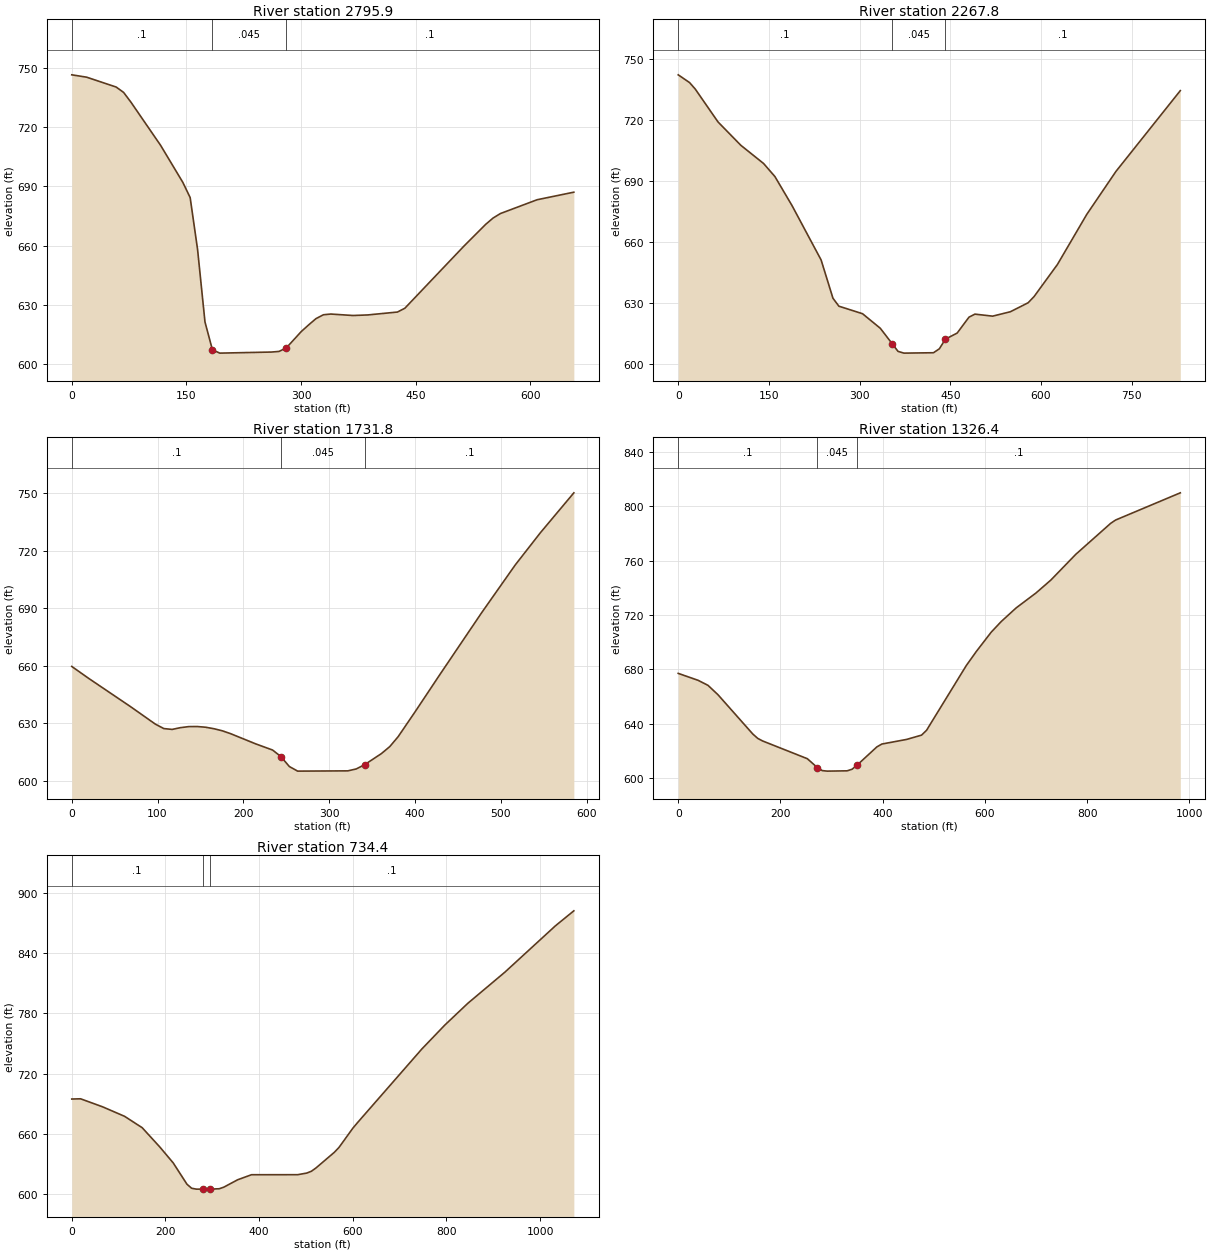
Type RM Length L Ch R = 1 ,2795.9  ,529.5,528.1,526.7
XS GIS Cut Line= 3
     1872186.201      551637.374     1872624.273      551792.782
     1872788.979       551891.54
#Sta/Elev= 30
       0  746.69    19.4   745.5    58.1  740.49    67.8  737.77    77.5  732.76
   116.2  710.91   145.3  692.11   154.9  684.36   164.6  658.04   174.3   621.2
     184   607.1   193.7   605.4   261.5  605.95   271.2  606.26   280.8  608.09
   300.2  616.33   309.9  619.73   319.6  622.93   329.2  624.87   338.9  625.24
     368   624.5   387.4  624.79   426.1  626.26   435.8  628.19   512.8  659.61
   541.6   670.8   551.2  673.97   560.8  676.26   608.9  683.28   656.9  687.11
#Mann= 3 , 0 , 0
       0      .1       0     184    .045       0   280.8      .1       0
Bank Sta=184,280.8
XS Rating Curve= 0 ,0
Exp/Cntr=0.3,0.1

Type RM Length L Ch R = 1 ,2267.8  ,531.1,536.1,541
XS GIS Cut Line= 4
     1871941.386      552002.744     1872067.775      552166.633
     1872434.442      552272.189     1872566.386      552474.966
#Sta/Elev= 30
       0  742.01    18.8  738.19    28.2     735    65.8  718.88   103.5  707.43
   141.1   698.5   159.9  692.08   188.2  677.83   236.3  651.14   255.9  632.35
   265.7  628.44   304.8  624.75   334.2   617.6   353.7  610.08   363.5  606.27
   373.3   605.4   422.2  605.59     432  607.56   441.8  612.26   461.3  615.24
   480.9  623.06   490.7  624.54     520  623.55   549.4  625.72   578.7  630.12
   588.5  633.15   627.2  648.93   675.6  673.46     724  694.62   830.4  734.25
#Mann= 3 , 0 , 0
       0      .1       0   353.7    .045       0   441.8      .1       0
Bank Sta=353.7,441.8
XS Rating Curve= 0 ,0
Exp/Cntr=0.3,0.1

Type RM Length L Ch R = 1 ,1731.8  ,394.8,405.3,415.9
XS GIS Cut Line= 2
     1871845.904      552591.647      1872359.09      552872.869
#Sta/Elev= 30
       0  659.71    19.5  653.55    68.3   638.8    97.5   629.6   107.3   627.3
     117  626.86   126.8  627.79   136.5  628.33   146.3  628.36     156     628
   165.8  627.21   175.6  626.12   185.3  624.61   214.6  619.28   234.1   616.1
   243.8  612.66   253.6   607.5   263.3   605.1   321.8  605.24   331.6  606.24
   341.4  608.48   360.9  614.25   370.6  617.87   380.4  623.06   399.9  635.87
   429.1  655.51   477.9  687.84   516.9  712.66   546.2  729.46   585.2  750.28
#Mann= 3 , 0 , 0
       0      .1       0   243.8    .045       0   341.4      .1       0
Bank Sta=243.8,341.4
XS Rating Curve= 0 ,0
Exp/Cntr=0.3,0.1

Type RM Length L Ch R = 1 ,1326.4  ,584.1,592,599.9
XS GIS Cut Line= 3
     1871655.659      552771.591     1871964.351      553219.651
     1872286.409      553516.833
#Sta/Elev= 30
       0  677.06    38.9  671.95    58.3  668.23    77.7  661.37   145.7   632.5
   155.5  629.21   165.2  627.29   252.6  614.25     272  607.77   281.8  605.48
   291.5   605.1   330.4  605.32   340.1  606.49   349.8  609.47   388.6  622.93
   398.4  625.04   446.9  628.44   476.1  631.61   485.8  635.14   563.6  682.84
   583.1  693.13   612.3  707.38   631.8  715.18     661  725.22   699.9  736.23
   729.1  745.78   777.8   764.7     846   787.5   855.7  789.95   982.3  809.98
#Mann= 3 , 0 , 0
       0      .1       0     272    .045       0   349.8      .1       0
Bank Sta=272,349.8
XS Rating Curve= 0 ,0
Exp/Cntr=0.3,0.1

Type RM Length L Ch R = 1 ,734.4   ,722.8,734.4,746
XS GIS Cut Line= 4
     1871240.603      552980.105     1871269.105      553184.827
     1871378.469      553603.492     1871413.398      554034.586
#Sta/Elev= 30
       0  694.67    18.8   694.9    65.8  686.92   112.7  677.48   150.3  666.15
   187.9  646.98   216.5  631.15     246  609.84   255.9  605.89   265.7     605
   279.2     605   294.2     605   314.9  605.37   324.7  606.97   354.2  614.32
   383.7  619.33   482.1  619.36   501.7  620.98   511.6  622.81   521.4  626.07
   560.7   641.7   570.6  646.55   600.1  665.65   609.9  671.09   747.5  744.52
   796.7   768.4   845.8  790.04   924.5  820.87  1032.6  867.08  1071.9  881.99
#Mann= 3 , 0 , 0
       0      .1       0   279.2    .045       0   294.2      .1       0
Bank Sta=279.2,294.2
XS Rating Curve= 0 ,0
Exp/Cntr=0.3,0.1

Chan Stop Cuts=-1
Use User Specified Reach Order=0
Composite Channel Slope=5